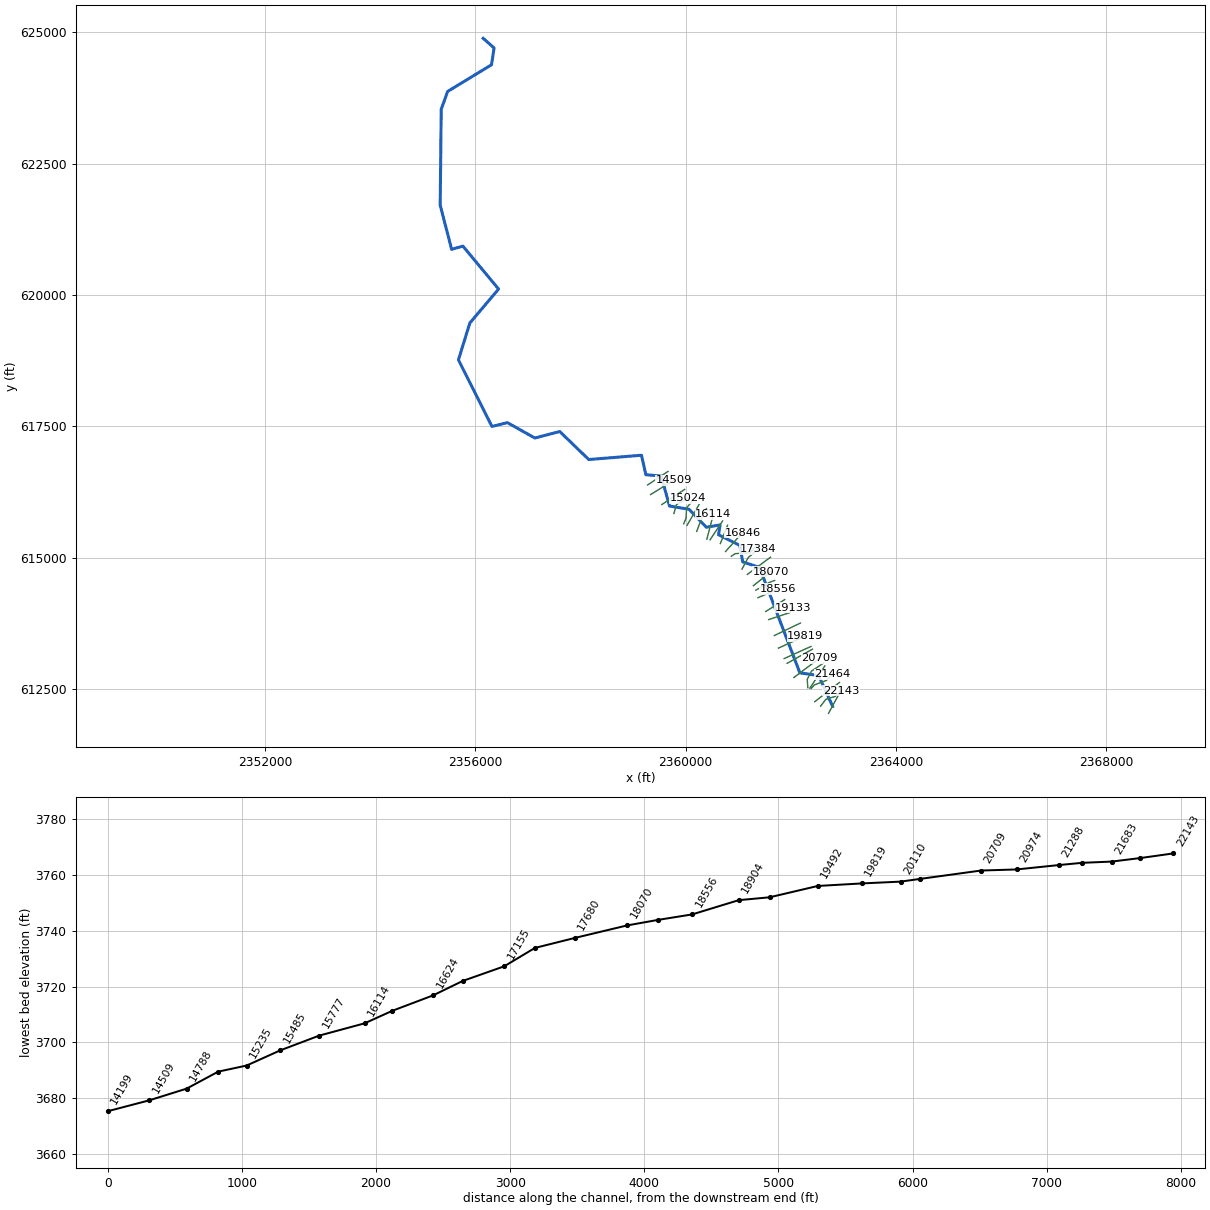
--- GNDYCK_2.prj (project) ---

Proj Title=GNDYCK_2
Current Plan=p01
Default Exp/Contr=0,0
English Units
Geom File=g01
Flow File=f01
Plan File=p01
BEGIN DESCRIPTION:
----------MODEL BY WOOD PLC 2022----------
AFH study
Randolph County, WV
HEC-RAS Version: RAS 6.2
Vertical Datum: NAVD88
Projection: NAD 1983 StatePlane West Virginia S FIPS 4702 (US Feet)
Terrain: 1-meter LIDAR (FEMA Region III 3DEP collected 2016-2018)
Land Use: 2019 NLCD
Hydrologic Method:
WV SIR2010-5033 regression equations
Additional Model Notes:
None
END DESCRIPTION:
DSS Export Rating Curves= 0
DSS Export Rating Curve Sorted= 0
DSS Export Volume Flow Curves= 0
DXF OffsetX= 0
DXF OffsetY= 0
DXF ScaleX= 0
DXF ScaleY= 0

--- GNDYCK_2.p01 (plan) ---

Plan Title=Floodplain
Program Version=6.20
Short Identifier=Floodplain
Geom File=g01
Flow File=f01
Subcritical Flow
K Sum by GR= 0
Std Step Tol= 0.01
Critical Tol= 0.01
Num of Std Step Trials= 20
Max Error Tol= 0.3
Flow Tol Ratio= 0.001
Split Flow NTrial= 30
Split Flow Tol= 0.02
Split Flow Ratio= 0.02
Log Output Level= 0
Friction Slope Method= 1
Unsteady Friction Slope Method= 2
Unsteady Bridges Friction Slope Method= 1
Parabolic Critical Depth
Global Vel Dist= 0 , 0 , 0
Global Log Level= 0
CheckData=True
Encroach Param=-1 ,0,0, 0
Mapping Interval=1HOUR
Computation Time Step Use Courant=        0
Computation Time Step Use Time Series=    0
Computation Time Step Count To Double=0
Computation Time Step Max Doubling=0
Computation Time Step Max Halving=0
Computation Time Step Residence Courant=0
Run HTab= 0
Run UNet= 0
Run Sediment= 0
Run PostProcess= 0
Run WQNet= 0
Run RASMapper=-1
UNET Theta= 0
UNET Theta Warmup= 0
UNET ZTol= 0
UNET ZSATol= 0
UNET MxIter= 0
UNET Max Iter WO Improvement= 0
UNET MaxInSteps= 0
UNET DtIC= 0
UNET DtMin= 0
UNET MaxCRTS= 0
UNET WFStab= 0
UNET SFStab= 0
UNET WFX= 1
UNET SFX= 1
UNET Gravity=32.174
UNET 1D Methodology=Finite Difference
UNET DSS MLevel= 1
UNET Pardiso=0
UNET DZMax Abort= 0
UNET Use Existing IB Tables= 0
UNET Froude Reduction=False
UNET Froude Limit= 0
UNET Froude Power= 0
UNET D1 Cores= 0
UNET WindReference=Eulerian
UNET WindDragFormulation=Hsu (1988)
UNET D2 Coriolis=0
UNET D2 Cores= 0
UNET D2 Theta= 1
UNET D2 Theta Warmup= 1
UNET D2 Z Tol= 0.01
UNET D2 Volume Tol= 0.01
UNET D2 Max Iterations= 20
UNET D2 Equation= 0
UNET D2 RampUpFraction=0.1
UNET D2 TimeSlices= 1
UNET D2 Turbulence Formulation=Non-Conservative (original)
UNET D2 Eddy Viscosity=0.3
UNET D2 Transverse Eddy Viscosity=0.1
UNET D2 Smagorinsky Mixing=0
UNET D2 BCVolumeCheck=0
UNET D2 Cores=0
UNET D2 SolverType=PARDISO (Direct)
UNET D2 Minimum Iterations= 2147483647
UNET D2 Maximum Iterations= 2147483647
UNET D2 Restart Number= 10
UNET D2 Relaxation Coeff=1.3
UNET D2 SOR Precondition Iterations= 10
UNET D2 ILUT Maximum Fill= 8
UNET D2 ILUT Tolerance=1E-08
UNET D1D2 MaxIter= 0
UNET D1D2 ZTol=0.01
UNET D1D2 QTol=0.1
UNET D1D2 MinQTol=1
Write IC File= 0
Write IC File at Fixed DateTime=0
Write IC File at Sim End=0
Echo Input=False
Echo Parameters=False
Echo Output=False
Write Detailed= 0
HDF Write Warmup=0
HDF Write Time Slices=0
HDF Flush=0
HDF Compression= 1
HDF Chunk Size= 1
HDF Spatial Parts= 1
HDF Use Max Rows=0
HDF Fixed Rows= 1
Calibration Method= 0
Calibration Iterations= 20
Calibration Max Change=0.05
Calibration Tolerance=0.2
Calibration Maximum=1.5
Calibration Minimum=0.5
Calibration Optimization Method= 1
WQ AD Non Conservative
WQ ULTIMATE=-1
WQ Max Comp Step=1HOUR
WQ Output Interval=15MIN
WQ Output Selected Increments= 0
WQ Output face flow=0
WQ Output face velocity=0
WQ Output face area=0
WQ Output face dispersion=0
WQ Output cell volume=0
WQ Output cell surface area=0
WQ Output cell continuity=0
WQ Output cumulative cell continuity=0
WQ Output face conc=0
WQ Output face dconc_dx=0
WQ Output face courant=0
WQ Output face peclet=0
WQ Output face adv mass=0
WQ Output face disp mass=0
WQ Output cell mass=0
WQ Output cell source sink temp=0
WQ Output nsm pathways=0
WQ Output nsm derived pathways=0
WQ Create Restart=0
WQ Fixed Restart=0
WQ System Summary=0
WQ Write To DSS=0
Sorting and Armoring Iterations= 10
XS Update Threshold= 0.02
Bed Roughness Predictor= 0
Hydraulics Update Threshold= 0.02
Energy Slope Method= 1
Volume Change Method= 1
Sediment Retention Method= 0
Sediment TS Multiplier= 1
Warm Up Method= 0
XS Weighting Method= 0
Number of US Weighted Cross Sections= 1
Number of DS Weighted Cross Sections= 1
Upstream XS Weight=0
Main XS Weight=1
Downstream XS Weight=0
Number of DS XS's Weighted with US Boundary= 1
Upstream Boundary Weight= 1
Weight of XSs Associated with US Boundary= 0
Number of US XS's Weighted with DS Boundary= 1
Downstream Boundary Weight= 0.5
Weight of XSs Associated with DS Boundary= 0.5
Percentile Method= 0
Sediment Output Level= 3
Mass or Volume Output= 0
Output Increment Type= 1
Profile and TS Output Increment= 1
Transport Output Increment 1
XS Output Flag= 0
XS Output Increment= 10
Read HDF5 Sediment Hotstart= 0
Sediment Hotstart Type= 0
Write Gradation File= 0
Read Gradation Hotstart= 0
Write HDF5 File= 1
Write Binary Output= 1
Write DSS Sediment File= 0
DSS Sediment Output Type= 1
SV Curve= 0
Specific Gage Flag= 0
Subcell Erosion Methods= 0
Subcell Deposition Methods= 0
Advection Scheme= 1
Matrix Solver= 0
Implicit Weighting Factor= 1
Maximum Outer Loop Convergence Iterations= 5
Convergence Maximum Absolute= 0.001
Convergence RMSE= 0.0001
Grain Fractions Max Abs Error= 0.001
Max Subgrid Regions= 1
Max Subgrid Length Scale= 3.402823E+38
Initial Layer Thickness= 3.402823E+38
Min Layer Thickness= 3.402823E+38
Max Layer Thickness= 3.402823E+38
Number of Layers= 5

--- GNDYCK_2.f01 (steady flow) ---

Flow Title=Flow
Program Version=6.20
Number of Profiles= 1
Profile Names=P100yr
River Rch & RM=GNDYCK_2,Main,22143
     457
River Rch & RM=GNDYCK_2,Main,20255
     509
River Rch & RM=GNDYCK_2,Main,16321
     593
River Rch & RM=GNDYCK_2,Main,12134
     662
River Rch & RM=GNDYCK_2,Main,8462
     764
River Rch & RM=GNDYCK_2,Main,3442
     939
Boundary for River Rch & Prof#=GNDYCK_2,Main            , 1
Up Type= 0
Dn Type= 3
Dn Slope=0.018
DSS Import GetInterval= 0
DSS Import GetPeak= 0
DSS Import FillOption= 0

--- GNDYCK_2.g01 (geometry) ---

Geom Title=Geometry
Program Version=6.20

River Reach=GNDYCK_2        ,Main
Reach XY= 30
2362795.22929801612167.3649011082362530.05724525 612753.17797003
     2362172.321      612804.529     2361403.476      614813.212
     2361084.379      614917.726     2361030.559      615231.268
     2360625.004      615434.3932360654.58948502615621.556425075
     2360391.858      615577.531     2360063.647       615918.72
     2359692.553      615980.786     2359533.698      616551.533
     2359242.466       616577.14     2359158.265        616947.8
2358155.18662258616866.063448792     2357603.574      617399.435
     2357130.278      617275.7512356606.71637187617568.976726547
2356313.27636513617495.9957547462355676.48130519618763.757640359
2355892.93308026619464.9963028552356440.10584059620111.354457804
2355761.26626973620929.354580418     2355546.667      620868.237
2355329.11732967621709.1414495522355348.64130519623533.877359641
2355470.50094555623873.3173896122356305.06408991624380.724550448
2356354.82883305624701.5530667812356146.90519002624884.506506022

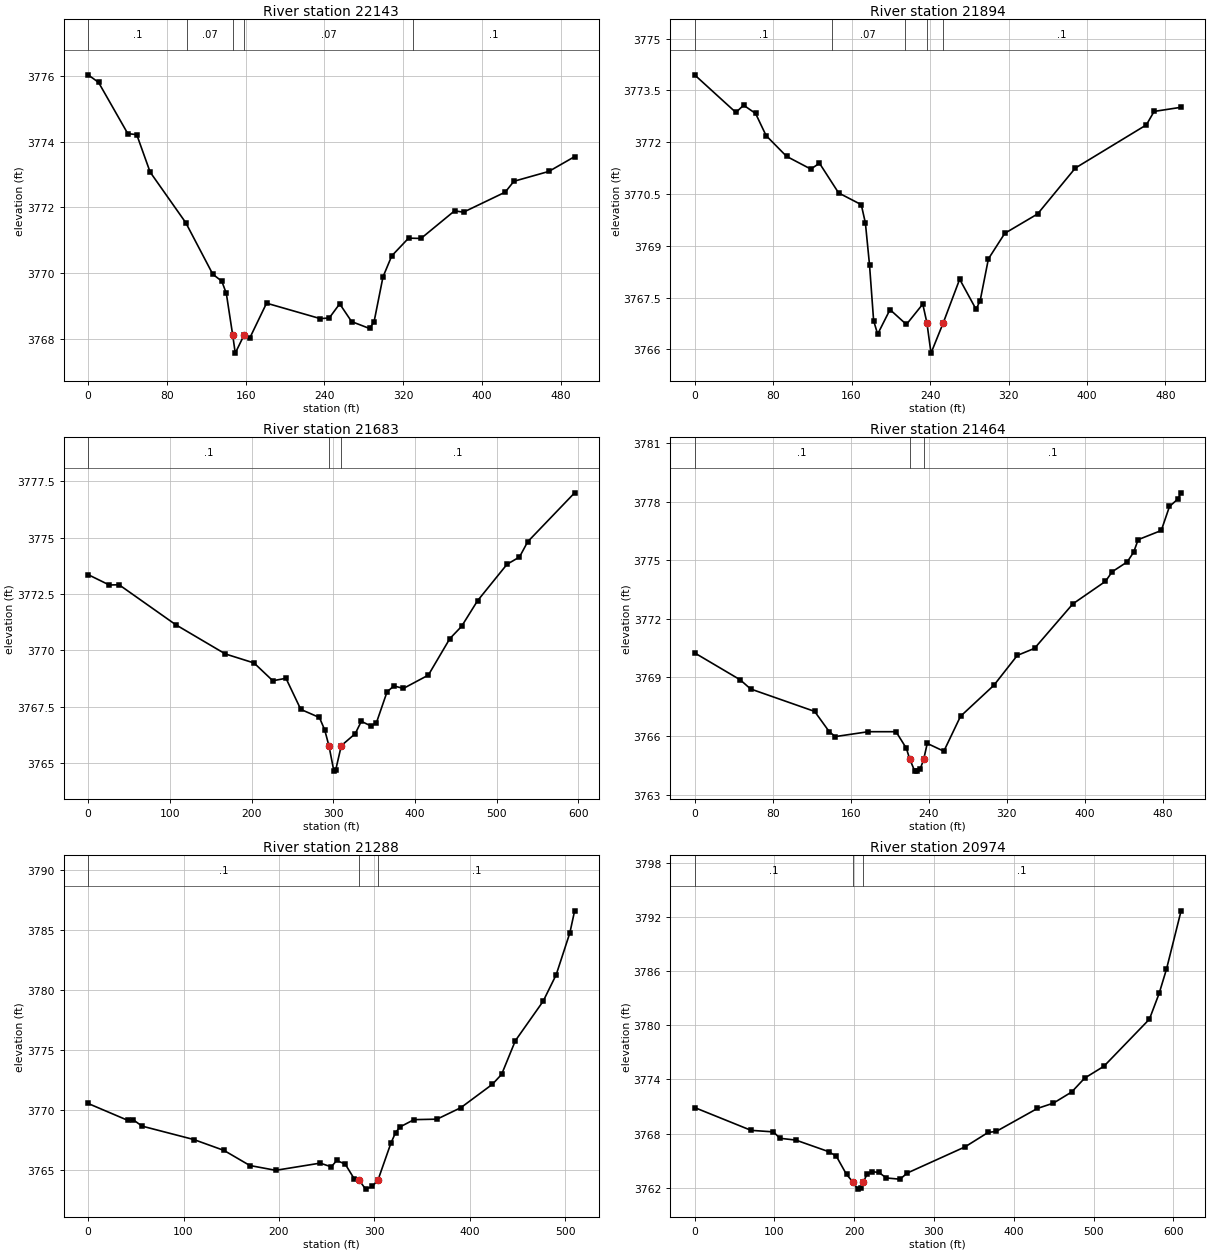
Type RM Length L Ch R = 1 ,22143   ,250.9,249,240
XS GIS Cut Line= 2
2362717.20534356612033.7307401632362952.47410565612468.437254459
#Sta/Elev= 30
       0 3776.03    10.6  3775.8    40.3 3774.24    49.4 3774.21      63 3773.07
    99.2 3771.53   126.7 3769.96   135.8 3769.75   140.4 3769.38  146.94  3768.1
   149.5 3767.56   158.6 3768.12   164.1 3768.01   181.3 3769.08   235.9 3768.61
     245 3768.63   255.6 3769.06   267.7 3768.52   285.9 3768.31   290.5 3768.51
   299.6 3769.88   308.5 3770.52   325.6 3771.06   338.2 3771.05   372.3 3771.89
   381.4 3771.85   423.8 3772.46   432.6 3772.79   468.1 3773.09   494.3 3773.54
#Mann= 5, -1 ,  0
       0     0.1       0     100    0.07       0  146.94   0.045       0
   158.6    0.07       0     330     0.1       0
Bank Sta=146.94,158.6
XS Rating Curve= 0 ,0
Exp/Cntr(USF)=0,0
Exp/Cntr=0.3,0.1

Type RM Length L Ch R = 1 ,21894   ,198.4,211.4,203.8
XS GIS Cut Line= 4
2362567.73967179612171.5740865582362666.63957128612302.558072596
2362845.85873066612356.8509355852362937.58492718 612468.45413674
#Sta/Elev= 30
       0 3773.95    42.1 3772.86      50 3773.07    62.2 3772.83    72.9 3772.19
    93.7 3771.59   118.5 3771.22   127.3 3771.39   146.8 3770.53   169.9 3770.19
   174.1 3769.66   178.3 3768.45   182.5 3766.83   186.6 3766.44   199.2 3767.15
   215.9 3766.72   232.6 3767.31   236.8 3766.77     241 3765.89   253.5 3766.77
   270.2 3768.03   286.9 3767.16   291.1 3767.41   299.5 3768.62   316.2 3769.36
   349.6 3769.92   388.1 3771.25   460.5  3772.5   468.4 3772.89   495.9 3773.01
#Mann= 5, -1 ,  0
       0     0.1       0     140    0.07       0  214.13     0.1       0
   236.8   0.045       0   253.5     0.1       0
Bank Sta=236.8,253.5
XS Rating Curve= 0 ,0
Exp/Cntr(USF)=0,0
Exp/Cntr=0.3,0.1

Type RM Length L Ch R = 1 ,21683   ,221.3,219.3,217
XS GIS Cut Line= 2
2362455.69919797 612256.464557592362925.47974696612622.144862463
#Sta/Elev= 30
       0 3773.36    25.9  3772.9    37.9 3772.91   107.1 3771.14   167.9 3769.84
     203 3769.44     226 3768.65   242.1 3768.76   260.2 3767.38     283 3767.02
   289.5 3766.47  294.82 3765.74   300.7 3764.64     303  3764.7   309.8 3765.77
   326.8  3766.3   334.3 3766.85   346.3 3766.64   352.8 3766.79   365.8 3768.16
   374.2 3768.42   385.8 3768.31   416.3  3768.9   442.6 3770.52   456.9 3771.06
   476.5  3772.2   512.6 3773.82   527.8 3774.14   537.9 3774.82   595.3 3776.99
#Mann= 3, -1 ,  0
       0     0.1       0  294.82   0.045       0   309.8     0.1       0
Bank Sta=294.82,309.8
XS Rating Curve= 0 ,0
Exp/Cntr(USF)=0,0
Exp/Cntr=0.3,0.1

Type RM Length L Ch R = 1 ,21464   ,166.3,175.4,177.2
XS GIS Cut Line= 4
 2362386.0871178612506.1947795822362446.82466879612574.886057484
  2362674.590485612660.2078553012362791.72719047612774.452296445
#Sta/Elev= 30
       0 3770.26    46.7 3768.88    57.4 3768.41     123 3767.26     138 3766.22
   144.2 3765.97     178 3766.22   206.4 3766.22     217 3765.37   220.43764.824
   225.5 3764.21   228.1  3764.2   231.2 3764.31  234.74  3764.8   238.4 3765.62
   255.4 3765.22   272.5 3767.01   306.7  3768.6   330.7 3770.13   348.3 3770.49
   387.6 3772.77   420.9 3773.92     428 3774.42   443.3 3774.92   449.9 3775.42
   454.5 3776.06   478.2 3776.53   486.6 3777.76   495.1 3778.14   498.5 3778.46
#Mann= 3, -1 ,  0
       0     0.1       0   220.4   0.045       0  234.74     0.1       0
Bank Sta=220.4,234.74
XS Rating Curve= 0 ,0
Exp/Cntr(USF)=0,0
Exp/Cntr=0.3,0.1

Type RM Length L Ch R = 1 ,21288   ,303.5,314,313.6
XS GIS Cut Line= 2
2362361.13781434612514.4265400992362647.00789124 612936.56454172
#Sta/Elev= 30
       0 3770.54    41.6 3769.13    47.4 3769.17    56.5 3768.65   110.7 3767.53
   142.4 3766.62   169.5 3765.36   196.6 3764.96   243.2 3765.56   254.8 3765.25
   260.5 3765.78   269.4 3765.48   278.7 3764.27   283.5 3764.19   290.8 3763.39
   297.9 3763.62  303.93 3764.19   317.3 3767.23   322.2 3768.11   326.8 3768.58
   341.5 3769.19   365.6 3769.23   390.6 3770.19   423.6 3772.14   433.3 3772.97
   447.7 3775.78   476.8 3779.07   490.5 3781.29   504.8 3784.78   509.8 3786.62
#Mann= 3, -1 ,  0
       0     0.1       0   283.5   0.045       0  303.93     0.1       0
Bank Sta=283.5,303.93
XS Rating Curve= 0 ,0
Exp/Cntr(USF)=0,0
Exp/Cntr=0.3,0.1

Type RM Length L Ch R = 1 ,20974   ,266.9,265.2,257.8
XS GIS Cut Line= 4
2362323.64092772612522.6040946092362311.69048697612682.767372483
 2362392.6072216612836.6998986412362620.09496906612991.465001213
#Sta/Elev= 30
       0 3770.88    70.8 3768.35    98.8 3768.18   106.9 3767.47   126.9 3767.27
   167.9 3765.99   177.6 3765.49   190.4 3763.46   198.63762.603   204.6 3761.83
   208.5 3761.94  211.27  3762.6   216.1 3763.47   221.8 3763.77   231.1 3763.68
   240.2 3763.07   257.5 3762.93   266.4 3763.61   338.8 3766.51   367.9 3768.12
     378 3768.23   429.6 3770.78   449.7 3771.37   472.7 3772.61   488.8 3774.14
     513 3775.46     570 3780.68   582.2 3783.54   591.4 3786.23   609.7  3792.7
#Mann= 3, -1 ,  0
       0     0.1       0   198.6   0.045       0  211.27     0.1       0
Bank Sta=198.6,211.27
XS Rating Curve= 0 ,0
Exp/Cntr(USF)=0,0
Exp/Cntr=0.3,0.1

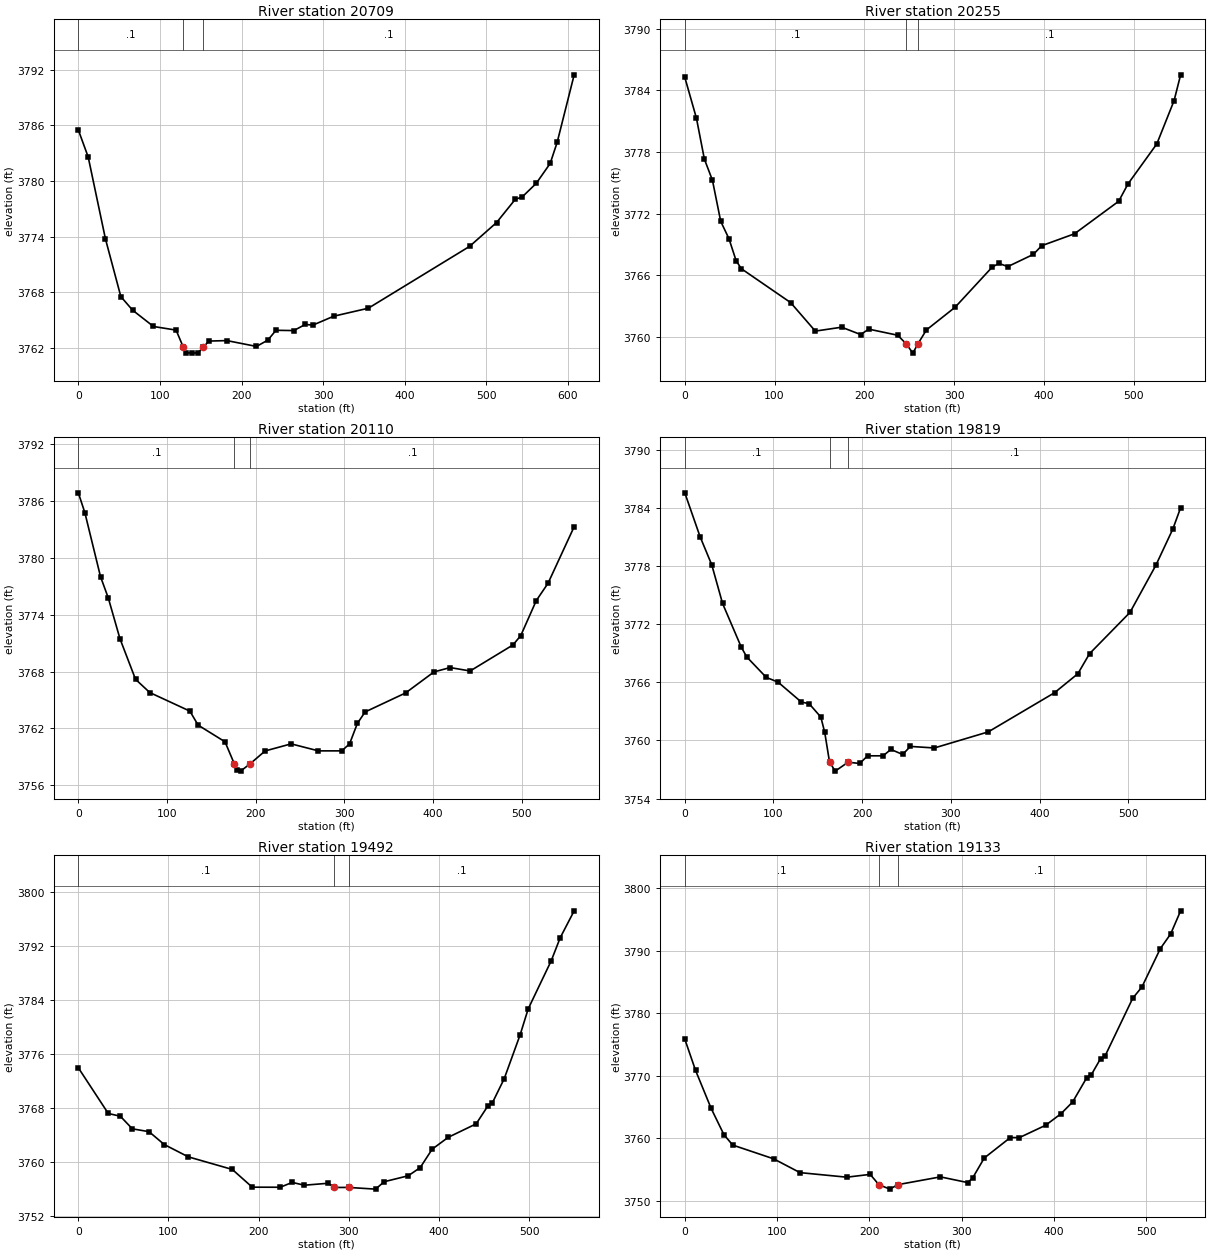
Type RM Length L Ch R = 1 ,20709   ,446.1,454,447
XS GIS Cut Line= 2
2362058.54006657612717.2123467422362544.32549088613082.139578904
#Sta/Elev= 30
       0 3785.49    12.1 3782.57    33.2 3773.76    52.1 3767.53    66.5 3766.07
    92.1 3764.31   119.8 3763.92  128.683762.071   132.1 3761.49   139.8 3761.44
   146.5 3761.47   153.1 3762.06   159.8 3762.74   182.1 3762.79   218.3 3762.16
   232.2 3762.84   242.2  3763.9     264 3763.87   278.3 3764.54   287.2 3764.45
     313 3765.42   355.4 3766.28   479.4 3772.94   512.5 3775.51   535.4 3778.01
   543.9 3778.27   561.1 3779.73   578.2 3781.88   586.8 3784.16   607.6 3791.43
#Mann= 3, -1 ,  0
       0     0.1       0  128.68   0.045       0   153.1     0.1       0
Bank Sta=128.68,153.1
XS Rating Curve= 0 ,0
Exp/Cntr(USF)=0,0
Exp/Cntr=0.3,0.1

Type RM Length L Ch R = 1 ,20255   ,140.3,145.3,135.2
XS GIS Cut Line= 2
2361929.26738413612986.3846623022362411.35420382613255.975071725
#Sta/Elev= 30
       0 3785.26      13 3781.27    21.8 3777.31    30.8 3775.25      40 3771.26
    49.2 3769.57    57.1 3767.45    62.9 3766.66   117.9 3763.36   145.4 3760.59
   174.7 3760.97   195.8 3760.26     205 3760.78   237.1 3760.19  246.67 3759.35
     254 3758.45   259.8 3759.37   269.1  3760.7   301.1 3762.91   342.5 3766.82
   349.9 3767.17   359.8 3766.86   388.3 3768.05   397.5 3768.89   434.1 3770.05
   483.3 3773.21   493.7  3774.9   525.8 3778.79     545 3782.99   552.3  3785.5
#Mann= 3, -1 ,  0
       0     0.1       0  246.67   0.045       0   259.8     0.1       0
Bank Sta=246.67,259.8
XS Rating Curve= 0 ,0
Exp/Cntr(USF)=0,0
Exp/Cntr=0.3,0.1

Type RM Length L Ch R = 1 ,20110   ,288.5,290.3,285.1
XS GIS Cut Line= 2
2361873.39686713613077.2875135862362383.04670413613307.413005629
#Sta/Elev= 30
       0 3786.88     7.4 3784.77      25 3778.03    33.8 3775.77    46.9 3771.48
    64.5 3767.18    80.6 3765.78   125.8 3763.82   135.1 3762.34   165.4 3760.58
  175.89 3758.26   178.6 3757.62     183 3757.48   194.1 3758.28   210.6 3759.61
     240 3760.36   270.8 3759.62   297.1 3759.62   305.9 3760.36   314.7 3762.52
   323.4 3763.73   369.1 3765.74   401.1 3767.96   419.3 3768.42   441.9 3768.06
   490.2 3770.81     499  3771.8   516.5  3775.5   529.7 3777.32   559.2  3783.3
#Mann= 3, -1 ,  0
       0     0.1       0  175.89   0.045       0   194.1     0.1       0
Bank Sta=175.89,194.1
XS Rating Curve= 0 ,0
Exp/Cntr(USF)=0,0
Exp/Cntr=0.3,0.1

Type RM Length L Ch R = 1 ,19819   ,322.1,327,319.9
XS GIS Cut Line= 2
2361764.47025663 613276.438563552362273.74072075613507.250720194
#Sta/Elev= 30
       0 3785.55    17.2 3781.03    30.4 3778.12    42.6 3774.13    63.8  3769.6
    69.9 3768.61    91.9  3766.5   105.1 3766.02   131.4 3763.96   140.2 3763.79
   153.4 3762.41   157.8 3760.82   163.23757.768   169.6 3756.83   184.1 3757.75
   197.3 3757.62   206.1 3758.41   223.6 3758.41   232.4 3759.07   245.6 3758.55
   254.4 3759.38   281.4 3759.22   342.2 3760.88   416.9 3764.92   443.2 3766.88
   456.4 3768.95     502 3773.21   531.1 3778.06   550.3 3781.81   559.1 3784.01
#Mann= 3, -1 ,  0
       0     0.1       0   163.2   0.045       0   184.1     0.1       0
Bank Sta=163.2,184.1
XS Rating Curve= 0 ,0
Exp/Cntr(USF)=0,0
Exp/Cntr=0.3,0.1

Type RM Length L Ch R = 1 ,19492   ,356.1,359.1,355.9
XS GIS Cut Line= 2
2361686.19766375613515.277397992 2362182.1597466613753.020142094
#Sta/Elev= 30
       0 3773.94    33.2 3767.16    46.6 3766.75    59.9 3764.88    78.4 3764.46
    95.3 3762.55     122 3760.72   170.8 3758.85   192.9 3756.22     224 3756.21
   237.3 3756.93   250.6 3756.51   277.2  3756.8  283.69 3756.18   299.8 3756.18
   329.7 3755.93   339.3 3757.03   365.9 3757.91   379.2 3759.12   392.5 3761.86
   410.3 3763.62   441.3 3765.62   454.6 3768.34   459.1 3768.69   472.4 3772.32
   490.1 3778.85     499 3782.68   524.6 3789.84   534.5 3793.24     550 3797.24
#Mann= 3, -1 ,  0
       0     0.1       0  283.69   0.045       0   299.8     0.1       0
Bank Sta=283.69,299.8
XS Rating Curve= 0 ,0
Exp/Cntr(USF)=0,0
Exp/Cntr=0.3,0.1

Type RM Length L Ch R = 1 ,19133   ,222.3,229.8,228.3
XS GIS Cut Line= 3
2361577.13838774613818.7279638662361978.36245648613950.663415888
2362046.62082424614042.873286359
#Sta/Elev= 30
       0 3775.88    11.6  3770.9    28.5 3764.81    42.4 3760.59    51.9 3758.93
    96.2 3756.73   124.8 3754.52   175.5 3753.79   200.8 3754.24   210.3 3752.58
   222.2 3751.88   230.6 3752.59   276.9 3753.84   306.4 3752.93   311.7 3753.64
   324.4 3756.86   352.7 3760.14   362.4 3760.12   390.9  3762.1   407.4 3763.93
   420.1 3765.82   435.4 3769.71   440.4 3770.19   450.4 3772.76   455.3  3773.2
   485.2 3782.42   495.2 3784.23   515.1 3790.36   526.3 3792.71   537.1 3796.41
#Mann= 3, -1 ,  0
       0     0.1       0   210.3   0.045       0   230.6     0.1       0
Bank Sta=210.3,230.6
XS Rating Curve= 0 ,0
Exp/Cntr(USF)=0,0
Exp/Cntr=0.3,0.1

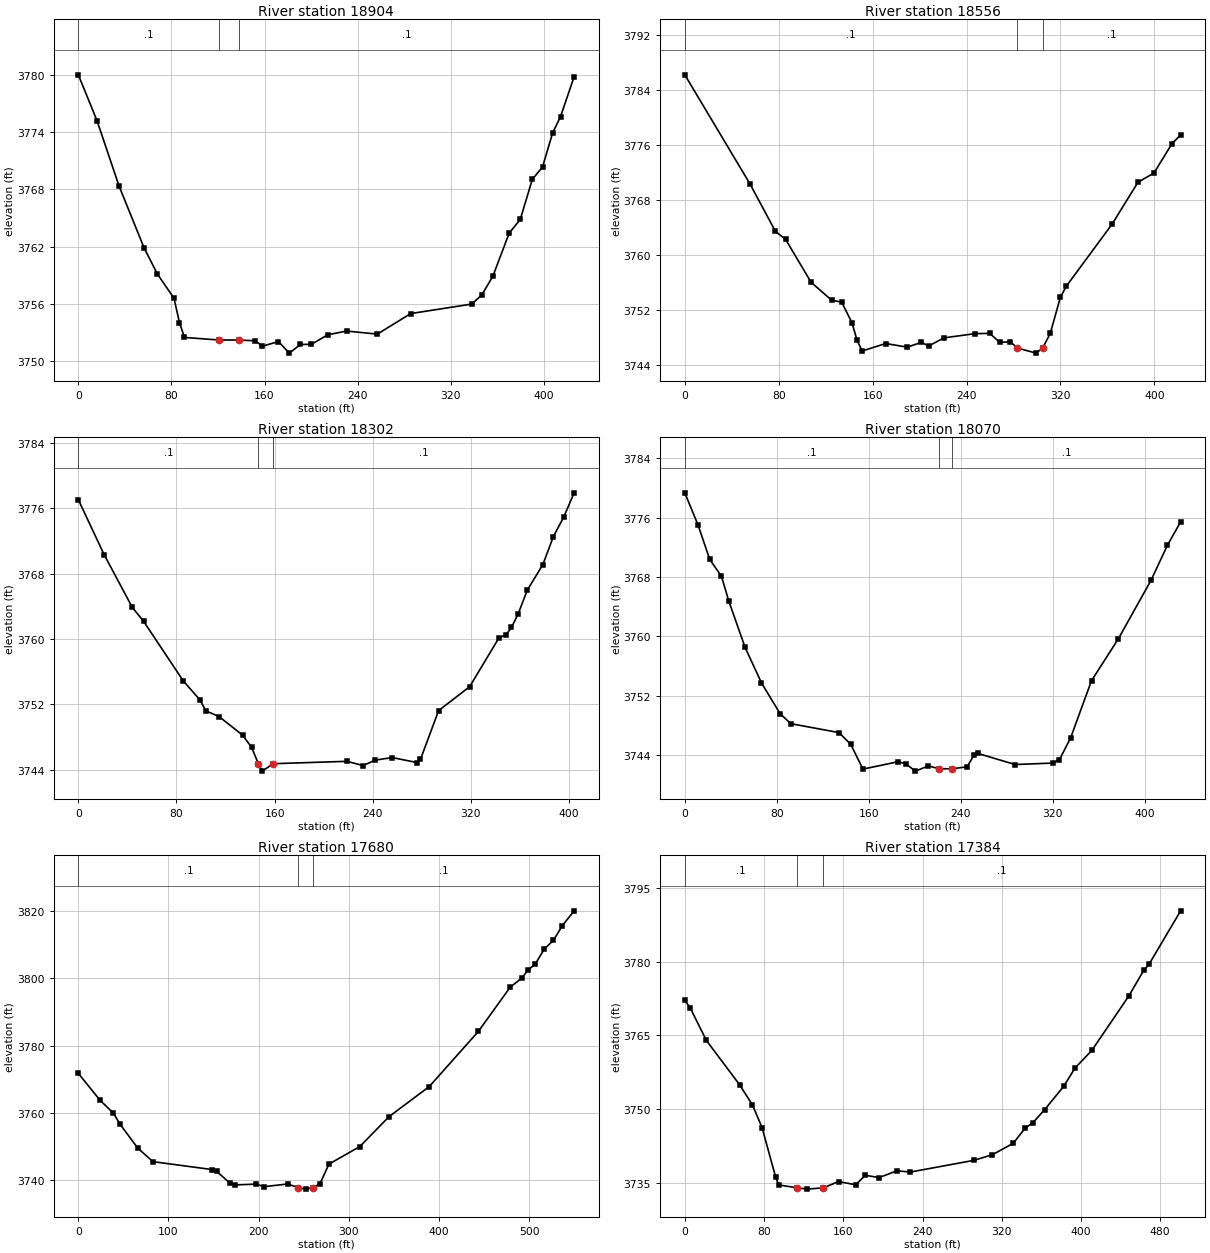
Type RM Length L Ch R = 1 ,18904   ,339.4,347.7,340.4
XS GIS Cut Line= 2
2361522.57247665613972.9959042962361883.45571289614199.442265079
#Sta/Elev= 30
       0 3779.98    16.1 3775.17    34.9 3768.37    56.4  3761.9      68 3759.12
    82.2  3756.6    86.9 3754.05    91.2  3752.5  121.053752.232   137.7 3752.23
   152.2 3752.15     158 3751.58   171.9 3752.07   181.3 3750.86   190.8 3751.77
   200.2 3751.78   214.4 3752.78   230.5 3753.17   256.9 3752.85   285.6    3755
   337.9 3755.99   346.6 3756.94   356.1 3758.89   370.2 3763.42   379.7 3764.85
   390.1 3769.06   398.8 3770.33   407.5  3773.9   414.3 3775.61     426 3779.79
#Mann= 3, -1 ,  0
       0     0.1       0  121.05   0.045       0   137.7     0.1       0
Bank Sta=121.05,137.7
XS Rating Curve= 0 ,0
Exp/Cntr(USF)=0,0
Exp/Cntr=0.3,0.1

Type RM Length L Ch R = 1 ,18556   ,235.9,253.8,249.4
XS GIS Cut Line= 2
2361373.21380636614235.4983306442361761.61503365614401.410679836
#Sta/Elev= 30
       0 3786.27    55.4 3770.43    77.2 3763.49    85.9 3762.31   107.6 3756.07
     125 3753.48   133.7 3753.17   142.4 3750.19   146.8  3747.6   151.1 3746.07
   171.2 3747.16   189.5 3746.63   201.6 3747.33   207.7 3746.79   220.7 3747.98
   247.4  3748.6   259.8 3748.63   268.5 3747.31   277.2 3747.43   283.4  3746.5
   299.2 3745.76  304.813746.487   311.4 3748.65   319.9 3753.86   325.1 3755.52
   364.2 3764.58     386 3770.62   399.7 3771.98     415 3776.24   422.4 3777.52
#Mann= 3, -1 ,  0
       0     0.1       0   283.4   0.045       0  304.81     0.1       0
Bank Sta=283.4,304.81
XS Rating Curve= 0 ,0
Exp/Cntr(USF)=0,0
Exp/Cntr=0.3,0.1

Type RM Length L Ch R = 1 ,18302   ,230.1,232.4,230
XS GIS Cut Line= 3
2361333.92790447614378.8322118332361596.46667895614528.642831279
2361692.01857018614564.006387587
#Sta/Elev= 30
       0 3777.05      21 3770.33      44 3763.86    53.2 3762.16    85.5 3754.87
    99.3  3752.5   103.9  3751.2   114.8 3750.48   133.9 3748.22   141.2 3746.73
  146.87 3744.68     150 3743.81   158.8 3744.72     219 3745.01   232.1 3744.49
   242.1 3745.16   255.9 3745.47   276.1 3744.86   278.9 3745.24   293.7 3751.22
     319 3754.15   342.9 3760.13   348.9 3760.54   353.1 3761.41   358.5 3763.04
   365.9 3765.95   378.7 3769.11   387.3 3772.54   395.9 3774.99   404.2 3777.89
#Mann= 3, -1 ,  0
       0     0.1       0  146.87   0.045       0   158.8     0.1       0
Bank Sta=146.87,158.8
XS Rating Curve= 0 ,0
Exp/Cntr(USF)=0,0
Exp/Cntr=0.3,0.1

Type RM Length L Ch R = 1 ,18070   ,378.6,389.5,384.9
XS GIS Cut Line= 2
  2361287.163162 614464.493829522361624.86310287614732.698022064
#Sta/Elev= 30
       0 3779.36    11.5 3775.03    21.7 3770.37    31.9  3768.1    38.2 3764.78
    52.4 3758.52    66.7 3753.71      83 3749.53    92.3 3748.21   134.1 3747.01
   144.3 3745.43   154.9 3742.08   185.2 3743.07     192 3742.82   200.5 3741.81
   211.9 3742.51  221.46 3742.12   232.6 3742.13   245.5 3742.39   251.7 3744.02
   254.6 3744.21   287.3  3742.7   320.1  3742.9   325.8 3743.35   335.5 3746.28
   353.7 3754.02     377 3759.65   405.5 3767.57   419.7 3772.28   431.2 3775.45
#Mann= 3, -1 ,  0
       0     0.1       0  221.46   0.045       0   232.6     0.1       0
Bank Sta=221.46,232.6
XS Rating Curve= 0 ,0
Exp/Cntr(USF)=0,0
Exp/Cntr=0.3,0.1

Type RM Length L Ch R = 1 ,17680   ,286.5,296.3,289.2
XS GIS Cut Line= 2
2361172.87795946614679.8521264662361614.67712881615007.439510159
#Sta/Elev= 30
       0 3771.76      24  3763.8      39  3759.9    46.2 3756.66    66.2 3749.45
    82.8 3745.51   148.5 3743.15   153.5 3742.63   168.4 3739.05   173.4 3738.59
     197 3738.83   206.3 3738.07   232.1 3738.87     244 3737.81   252.1 3737.34
   260.7 3737.81     268 3738.92     278 3744.79   312.1 3749.97   344.7  3758.9
   389.3 3767.85   443.7 3784.22     479 3797.38   492.1 3800.15   499.2 3802.62
   506.6 3804.16     517 3808.78     527 3811.32   536.9  3815.7     550  3820.1
#Mann= 3, -1 ,  0
       0     0.1       0     244   0.045       0   260.7     0.1       0
Bank Sta=244,260.7
XS Rating Curve= 0 ,0
Exp/Cntr(USF)=0,0
Exp/Cntr=0.3,0.1

Type RM Length L Ch R = 1 ,17384   ,234.7,228.6,213.8
XS GIS Cut Line= 3
2361071.32057628614780.4643460062361188.63041567614999.000087591
2361380.48554907615163.252343765
#Sta/Elev= 30
       0 3772.13     5.4  3770.6    21.8 3763.97    55.3 3754.98    68.3 3750.88
      78 3746.28    91.6 3736.31    94.8 3734.63   113.4 3734.05   123.4 3733.78
     140 3734.05   155.2 3735.32   172.5 3734.66   182.4 3736.59   196.1 3736.12
   214.2  3737.5   227.8 3737.25   291.8 3739.62   310.6 3740.77   331.7  3743.1
   343.6 3746.17   351.4 3747.25   363.3 3749.92   382.6 3754.66   393.9 3758.35
     411 3761.96   448.2 3772.97   463.3 3778.18   468.6  3779.4   500.6 3790.29
#Mann= 3, -1 ,  0
       0     0.1       0   113.4   0.045       0     140     0.1       0
Bank Sta=113.4,140
XS Rating Curve= 0 ,0
Exp/Cntr(USF)=0,0
Exp/Cntr=0.3,0.1

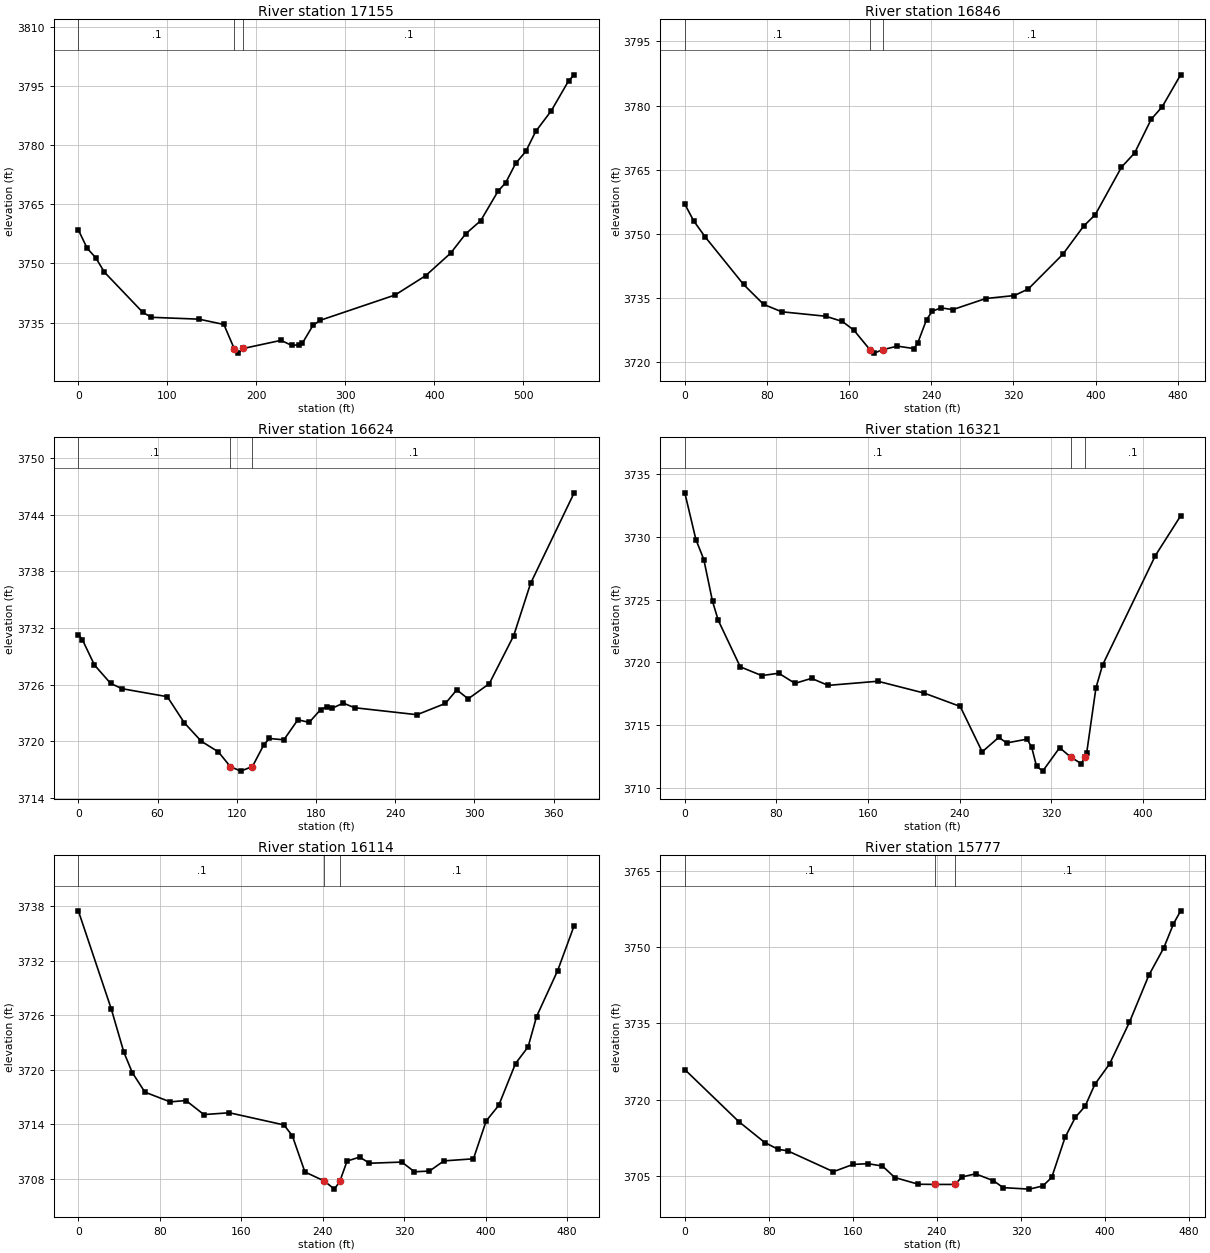
Type RM Length L Ch R = 1 ,17155   ,304.4,309.3,312.2
XS GIS Cut Line= 4
2360867.96555501 615024.78762083 2360942.3713179615074.690711034
2361224.77907752615092.6078196512361354.33638452615223.919800016
#Sta/Elev= 30
       0 3758.54     9.9 3753.86    19.5 3751.47    29.3 3747.79    72.5 3737.56
    82.1 3736.32   135.5 3735.85   163.5  3734.5  175.12 3728.36   179.6 3727.22
  185.33  3728.4   227.7 3730.47   239.7 3729.17   247.7 3729.35   251.7 3729.76
   263.7  3734.3   271.8 3735.56   355.9 3741.99   390.2  3746.9   418.3 3752.63
   435.2 3757.54     452 3760.86   471.5 3768.37   480.1 3770.51   491.3 3775.43
   502.7 3778.47   513.8 3783.54   531.2 3788.75   550.7 3796.37     557 3797.92
#Mann= 3, -1 ,  0
       0     0.1       0  175.12   0.045       0  185.33     0.1       0
Bank Sta=175.12,185.33
XS Rating Curve= 0 ,0
Exp/Cntr(USF)=0,0
Exp/Cntr=0.3,0.1

Type RM Length L Ch R = 1 ,16846   ,220.3,221.6,225.8
XS GIS Cut Line= 2
2360758.02371839615114.9574531752361080.20303905615474.479241372
#Sta/Elev= 30
       0 3756.89     8.8 3752.92    20.1 3749.14    57.2 3738.08    76.7 3733.42
    94.3 3731.68   137.3 3730.63   153.4 3729.41   164.6 3727.38   180.2 3722.81
   184.4 3721.99   192.9  3722.8     207 3723.63   223.2 3723.05   226.9 3724.42
   235.4 3729.84     241 3731.81   249.5  3732.6   260.9 3732.18     293 3734.78
   320.9 3735.48   334.5 3737.03   368.2 3745.17   388.3 3751.73   399.7 3754.43
   425.2 3765.55     438 3768.88   454.2  3776.8   464.9 3779.72   482.8 3787.19
#Mann= 3, -1 ,  0
       0     0.1       0   180.2   0.045       0   192.9     0.1       0
Bank Sta=180.2,192.9
XS Rating Curve= 0 ,0
Exp/Cntr(USF)=0,0
Exp/Cntr=0.3,0.1

Type RM Length L Ch R = 1 ,16624   ,299.8,303.3,291.3
XS GIS Cut Line= 2
2360659.01912608615266.501403941 2360796.8664253615615.881705709
#Sta/Elev= 30
       0  3731.3       3 3730.77    12.2 3728.07    24.4 3726.13      33 3725.56
    67.4 3724.71    80.3 3721.94    93.2 3719.98   106.1 3718.86  115.07 3717.31
     123 3716.82   131.9 3717.31   140.5 3719.61   144.7 3720.28   155.7 3720.14
   166.3 3722.26   174.9 3721.99   183.5 3723.34     188 3723.63   192.1 3723.47
   200.7 3724.03   209.3 3723.54   256.6  3722.8   278.1    3724   286.7 3725.44
   295.3 3724.48   311.3 3726.09   329.8 3731.18   342.6 3736.72   375.6 3746.32
#Mann= 3, -1 ,  0
       0     0.1       0  115.07   0.045       0   131.9     0.1       0
Bank Sta=115.07,131.9
XS Rating Curve= 0 ,0
Exp/Cntr(USF)=0,0
Exp/Cntr=0.3,0.1

Type RM Length L Ch R = 1 ,16321   ,204.8,206.9,208.1
XS GIS Cut Line= 2
2360463.01664629615336.8582679212360702.25332567615697.498635335
#Sta/Elev= 30
       0 3733.52     9.7 3729.79    16.6  3728.2    24.2 3724.86    29.2 3723.35
    48.4 3719.64    67.2 3718.94      82 3719.13    96.2 3718.32   110.6 3718.72
   125.1 3718.16   168.5 3718.49   208.8 3717.55   240.4 3716.48   259.6 3712.86
     274 3714.01     281 3713.57   298.8 3713.87   302.8 3713.22     307 3711.72
   312.4 3711.32   327.2 3713.19   336.73712.449     346 3711.92  349.53 3712.45
   350.8 3712.77   358.9 3717.97   364.7 3719.79   410.8 3728.52   432.8 3731.68
#Mann= 3, -1 ,  0
       0     0.1       0   336.7   0.045       0  349.53     0.1       0
Bank Sta=336.7,349.53
XS Rating Curve= 0 ,0
Exp/Cntr(USF)=0,0
Exp/Cntr=0.3,0.1

Type RM Length L Ch R = 1 ,16114   ,325.3,337.1,330.8
XS GIS Cut Line= 2
2360402.38634225 615349.920483612360525.90457036615820.857799421
#Sta/Elev= 30
       0 3737.49    32.3  3726.7    44.7 3721.92      53 3719.67    65.4 3717.52
    90.2 3716.45   105.7  3716.6   123.3 3715.05   148.3 3715.25   201.9 3713.91
   210.1 3712.73   222.5 3708.73   241.53707.737   251.5 3706.84   256.83707.705
   263.9 3709.93   276.3 3710.37   285.9 3709.69   317.7 3709.82   330.1 3708.75
   344.8 3708.83     359 3709.95     388 3710.18   400.5 3714.35   412.8 3716.06
   429.3 3720.67   441.7 3722.51     450 3725.85   470.7 3730.91   486.9 3735.86
#Mann= 3, -1 ,  0
       0     0.1       0   241.5   0.045       0   256.8     0.1       0
Bank Sta=241.5,256.8
XS Rating Curve= 0 ,0
Exp/Cntr(USF)=0,0
Exp/Cntr=0.3,0.1

Type RM Length L Ch R = 1 ,15777   ,281.8,291.6,284.7
XS GIS Cut Line= 3
 2360209.5365386615497.8836611352360335.30458989615835.014218075
2360393.40690501615930.999382383
#Sta/Elev= 30
       0 3725.94    51.3 3715.74    76.1 3711.62    88.9 3710.28    97.9 3709.99
   141.4 3705.89   160.1 3707.32   174.3 3707.46   188.1 3707.01   199.9 3704.75
   222.3 3703.43   238.3 3703.39  257.123703.392   263.9 3704.86   276.8 3705.47
   293.8 3704.12   303.1 3702.76     328 3702.47   340.8 3703.09   349.3 3704.77
     362 3712.63   371.7 3716.53   381.1 3718.75   390.4 3723.06   404.4 3727.05
   423.3 3735.24   441.8 3744.47   455.9 3749.79   465.2 3754.53     472 3757.09
#Mann= 3, -1 ,  0
       0     0.1       0   238.3   0.045       0  257.12     0.1       0
Bank Sta=238.3,257.12
XS Rating Curve= 0 ,0
Exp/Cntr(USF)=0,0
Exp/Cntr=0.3,0.1

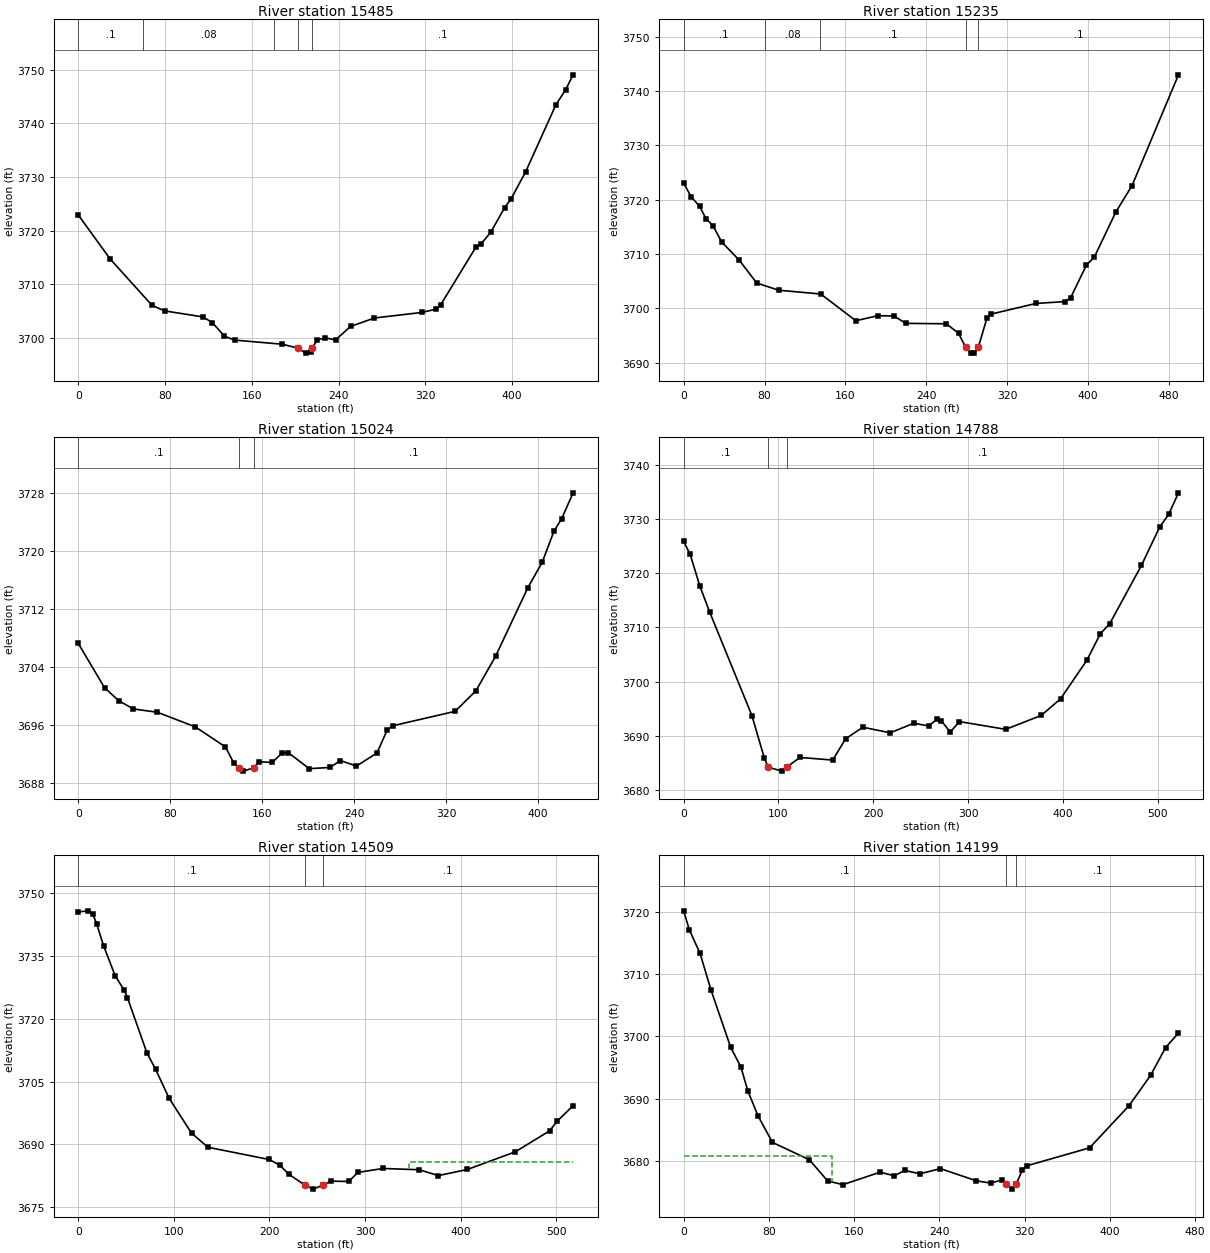
Type RM Length L Ch R = 1 ,15485   ,244.6,250.5,248.5
XS GIS Cut Line= 2
2360024.93566533615611.6234622782360252.47790304616007.076350589
#Sta/Elev= 30
       0 3722.93    29.5  3714.7      68 3706.08    79.7 3705.05     115 3703.93
   123.6 3702.86   134.8 3700.34   144.1 3699.61   188.1 3698.84   202.7  3698.1
   209.5 3697.18   214.1 3697.42  215.743698.153   220.3 3699.66   227.9 3700.02
   237.2 3699.65     251 3702.15     273 3703.73     317 3704.77   329.5 3705.36
   334.1 3706.18   366.4 3716.88     371 3717.47   380.2 3719.68   393.1 3724.32
     399 3725.93   412.5 3731.01   440.2 3743.42   449.4 3746.32   456.2 3749.06
#Mann= 5, -1 ,  0
       0     0.1       0      60    0.08       0     180     0.1       0
   202.7   0.045       0  215.74     0.1       0
Bank Sta=202.7,215.74
XS Rating Curve= 0 ,0
Exp/Cntr(USF)=0,0
Exp/Cntr=0.3,0.1

Type RM Length L Ch R = 1 ,15235   ,212.3,211.2,209.5
XS GIS Cut Line= 4
 2359962.1091272615642.442136395 2360006.1805181615748.615700077
2360018.13722024615949.5977944222360132.13084075616079.678256668
#Sta/Elev= 30
       0 3723.07     7.3 3720.57    15.9 3718.75      22 3716.52    28.9 3715.24
    37.6 3712.23    54.9 3708.88    72.3 3704.66    93.9 3703.34   135.6 3702.64
   170.3 3697.72   191.7 3698.64   207.7 3698.61   219.7 3697.24   259.8 3697.16
   271.8 3695.41  278.88 3692.83   283.8 3691.81   287.6 3691.76   291.4 3692.85
   299.8 3698.14   303.9 3698.94   348.6 3700.91     377 3701.24   382.6 3701.94
   398.3 3707.96   406.2 3709.48   427.4 3717.74   443.4  3722.6   489.3 3742.98
#Mann= 5, -1 ,  0
       0     0.1       0      80    0.08       0  134.96     0.1       0
  278.88   0.045       0   291.4     0.1       0
Bank Sta=278.88,291.4
XS Rating Curve= 0 ,0
Exp/Cntr(USF)=0,0
Exp/Cntr=0.3,0.1

Type RM Length L Ch R = 1 ,15024   ,243.2,235.8,230.4
XS GIS Cut Line= 3
2359775.67636873615839.1328590562359825.56792847616011.945652936
2360046.82614992616129.805424494
#Sta/Elev= 30
       0 3707.23    22.9  3701.1    35.4  3699.3    47.9 3698.18    68.7 3697.73
   101.8 3695.71   128.1 3692.93   135.4 3690.68   139.5 3690.05   143.7 3689.59
  152.74 3690.05   157.1 3690.88   168.7 3690.79     177 3692.04   182.7 3692.15
     201 3689.93   219.1  3690.1   228.1 3691.05   242.1 3690.29   259.9 3692.09
   268.9  3695.3   273.5 3695.85   327.9 3697.85     346 3700.68   363.1 3705.45
   391.3 3714.96   403.7 3718.44     414 3722.76   420.7 3724.48   430.6 3728.04
#Mann= 3, -1 ,  0
       0     0.1       0   139.5   0.045       0  152.74     0.1       0
Bank Sta=139.5,152.74
XS Rating Curve= 0 ,0
Exp/Cntr(USF)=0,0
Exp/Cntr=0.3,0.1

Type RM Length L Ch R = 1 ,14788   ,279.8,278.6,279
XS GIS Cut Line= 2
 2359545.8859354616009.3743205712359980.78048804 616297.95861711
#Sta/Elev= 30
       0 3725.84     6.9 3723.45    17.1 3717.61    27.5  3712.8      72 3693.75
    85.2 3685.85    89.2 3684.24   103.6 3683.51   108.7 3684.25   122.7 3686.03
   157.3 3685.55   170.8 3689.47   189.1  3691.6   217.9 3690.57   242.8 3692.34
   258.3 3691.84   267.3 3693.06   271.6 3692.84   281.2  3690.7   290.8 3692.64
   339.7 3691.21   377.2 3693.78   397.5 3696.83   425.2 3703.92   439.6 3708.86
   449.2 3710.62   482.8 3721.41     502 3728.47   511.6 3730.84   521.9  3734.8
#Mann= 3, -1 ,  0
       0     0.1       0    89.2   0.045       0   108.7     0.1       0
Bank Sta=89.2,108.7
XS Rating Curve= 0 ,0
Exp/Cntr(USF)=0,0
Exp/Cntr=0.3,0.1

Type RM Length L Ch R = 1 ,14509   ,308.3,309.9,302
XS GIS Cut Line= 2
2359331.34638907616199.2901409932359771.79271699 616471.25317492
#Sta/Elev= 30
       0  3745.5    10.4 3745.77    15.1 3745.06    19.4 3742.53    26.4 3737.47
    38.6 3730.24      48 3726.85    51.4 3725.06    71.7 3711.91    80.9 3707.93
      95 3701.03   118.5 3692.69   135.7 3689.32   199.6 3686.41   211.2 3684.99
     220 3682.92   237.4 3680.24   245.4 3679.33  256.023680.257   264.2 3681.23
     283 3681.16   292.4 3683.32   318.8 3684.26   356.6 3683.96   376.7 3682.56
   407.1 3684.03     457 3688.22   493.2 3693.27   500.6 3695.49   517.6 3699.24
#Mann= 3, -1 ,  0
       0     0.1       0   237.4   0.045       0  256.02     0.1       0
#XS Ineff= 2 , 0
                          345.59         3685.72
Permanent Ineff=
       F       F
Bank Sta=237.4,256.02
XS Rating Curve= 0 ,0
Exp/Cntr(USF)=0,0
Exp/Cntr=0.3,0.1

Type RM Length L Ch R = 1 ,14199   ,284.3,287.8,287.7
XS GIS Cut Line= 2
2359275.37232202 616382.477157182359662.28574314 616639.31637667
#Sta/Elev= 30
       0  3720.2     5.4 3717.11    15.4 3713.36    25.6  3707.5    44.2 3698.22
    53.8 3695.06    60.2 3691.24      70 3687.16    83.3 3682.96     118 3680.16
   135.1 3676.76   149.5 3676.16   184.3 3678.16   197.8 3677.59   207.4 3678.44
   221.9 3677.91     241 3678.74   274.6 3676.78   288.2 3676.41   298.6 3676.91
   302.6 3676.32   308.2 3675.44  312.25 3676.27   317.8 3678.51   322.6 3679.22
     381 3682.08   418.1 3688.88   438.3 3693.76   452.3  3698.2   464.4 3700.56
#Mann= 3, -1 ,  0
       0     0.1       0   302.6   0.045       0  312.25     0.1       0
#XS Ineff= 2 , 0
          138.96 3680.79
Permanent Ineff=
       F       F
Bank Sta=302.6,312.25
XS Rating Curve= 0 ,0
Exp/Cntr(USF)=0,0
Exp/Cntr=0.3,0.1