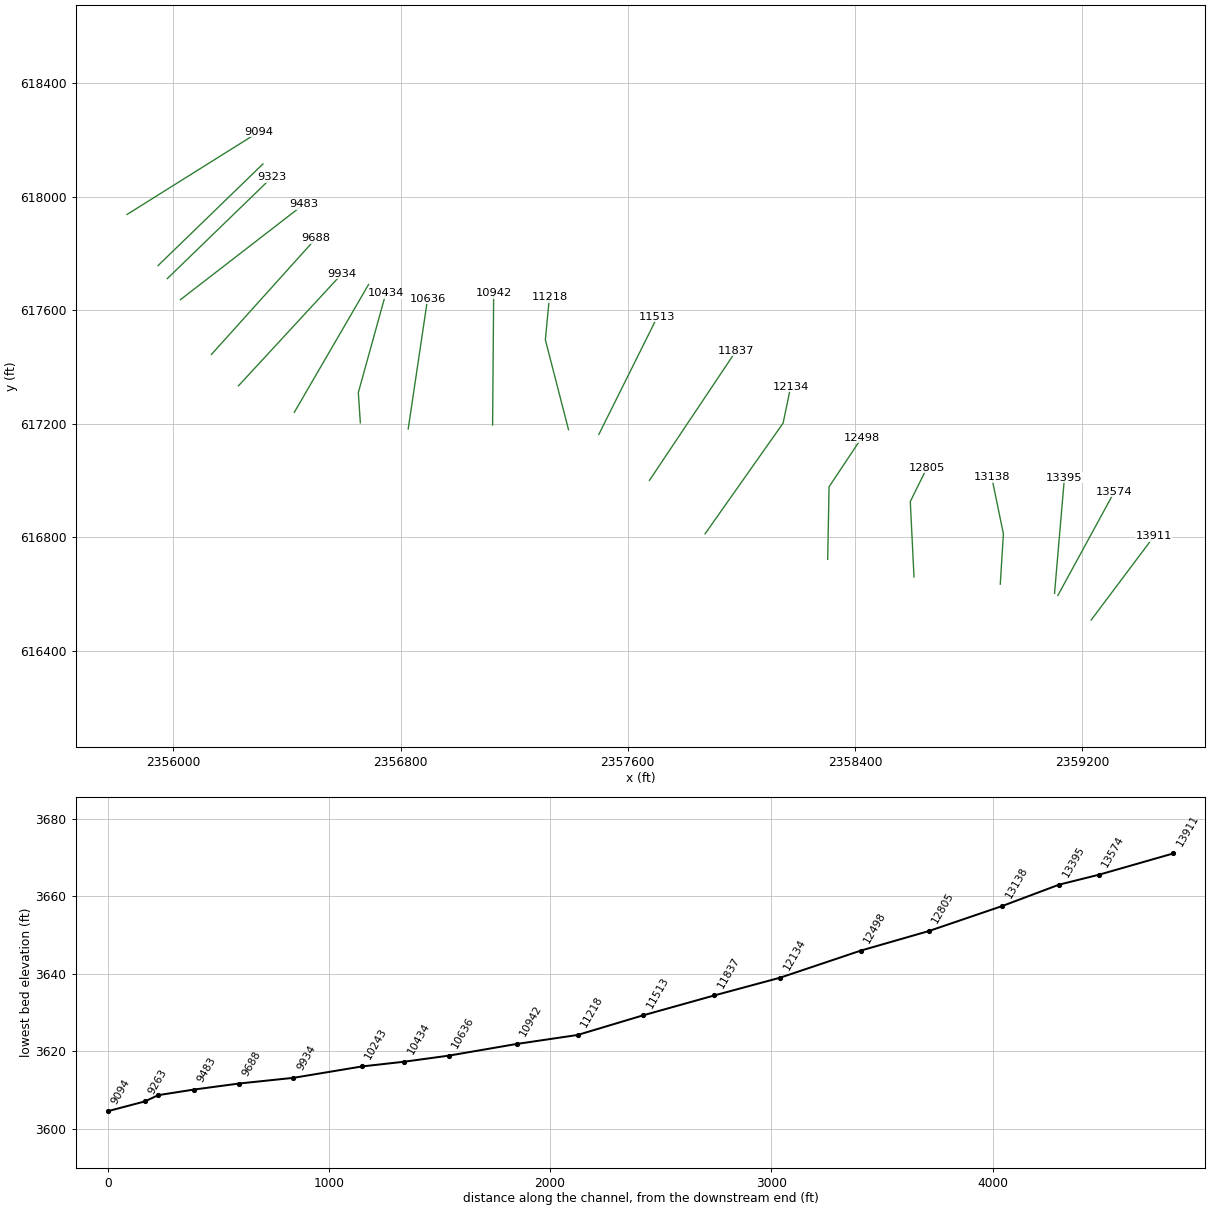
HEC-RAS study GNDYCK_2.prj: GNDYCK_2

--- GNDYCK_2.g01 (geometry) --- (continued)

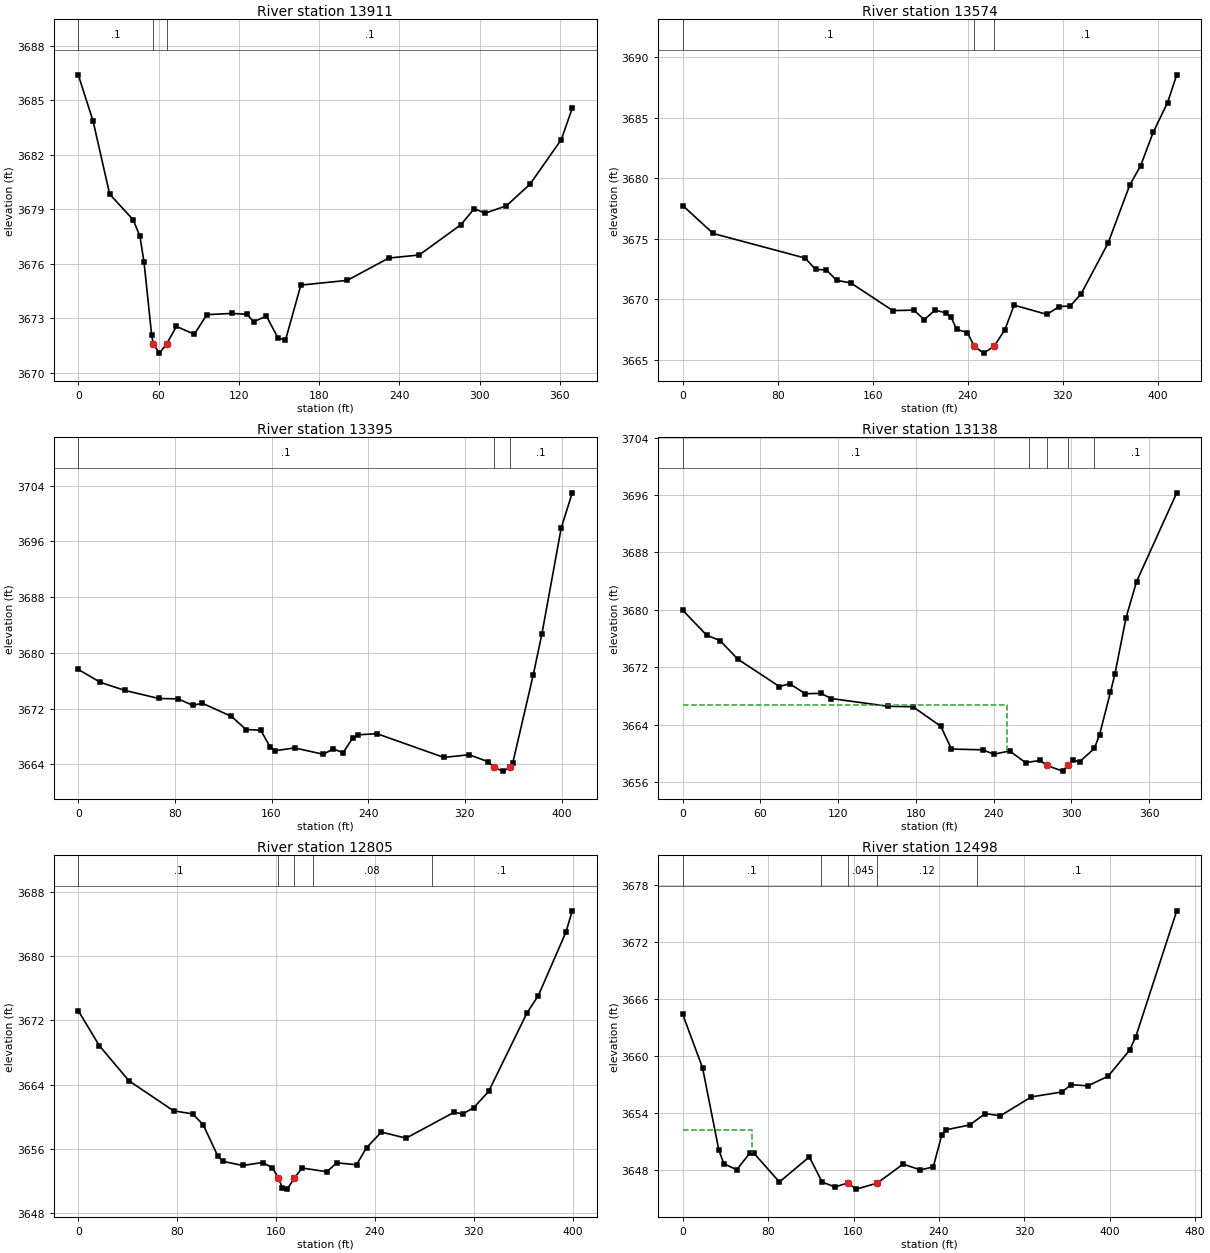
Type RM Length L Ch R = 1 ,13911   ,329.2,337.4,336.9
XS GIS Cut Line= 2
2359232.10428196616508.3345574682359453.68941361616803.738345423
#Sta/Elev= 30
       0 3686.41    11.1 3683.86    23.5 3679.83    41.1 3678.42    46.1 3677.51
    49.2 3676.07    54.9 3672.05    56.1 3671.56    60.7 3671.07    66.1 3671.58
    73.4 3672.54    86.8 3672.11    96.1 3673.19   114.9 3673.26   126.1 3673.21
   131.1  3672.8   140.7 3673.11   149.2 3671.92   154.9 3671.78   166.4 3674.82
   201.1 3675.08   232.1 3676.31   254.9 3676.48   286.1 3678.15   296.1 3679.04
     304 3678.78   320.1 3679.19   337.8 3680.39   361.1 3682.84   369.3 3684.57
#Mann= 3, -1 ,  0
       0     0.1       0    56.1   0.045       0    66.1     0.1       0
Bank Sta=56.1,66.1
XS Rating Curve= 0 ,0
Exp/Cntr(USF)=0,0
Exp/Cntr=0.3,0.1

Type RM Length L Ch R = 1 ,13574   ,174.3,179.5,178.9
XS GIS Cut Line= 2
 2359114.7939687616594.7369159792359313.63714157616959.885287985
#Sta/Elev= 30
       0 3677.75    25.6 3675.44     103 3673.41   111.9 3672.47   120.8 3672.43
   129.6 3671.57   141.4 3671.36   176.8 3669.07   194.5 3669.11   203.3 3668.32
   212.3 3669.11   221.4 3668.89     226 3668.52   230.5 3667.52   239.6 3667.26
   245.4 3666.12   253.3 3665.56   262.2 3666.13   271.2  3667.5   278.9 3669.52
   306.5 3668.76   317.1 3669.41   326.2 3669.45   335.3 3670.45     358 3674.64
   376.3 3679.45   385.4 3681.03     396  3683.8   408.1 3686.25   415.8 3688.54
#Mann= 3, -1 ,  0
       0     0.1       0   245.4   0.045       0   262.2     0.1       0
Bank Sta=245.4,262.2
XS Rating Curve= 0 ,0
Exp/Cntr(USF)=0,0
Exp/Cntr=0.3,0.1

Type RM Length L Ch R = 1 ,13395   ,252.6,256.7,257.3
XS GIS Cut Line= 2
2359103.20423164 616602.814808192359138.09705229617010.267232931
#Sta/Elev= 30
       0 3677.61    18.4 3675.75    38.5  3674.6    66.6 3673.44    82.7 3673.38
    94.7 3672.46   102.7 3672.75   126.8 3670.87   138.9 3668.98     151 3668.89
   158.9 3666.46     163 3665.94     179 3666.34   202.8 3665.43   211.1  3666.2
   219.2 3665.64   227.2 3667.77   231.2 3668.22   247.3 3668.38   302.6 3664.98
   323.5 3665.36   339.5 3664.35     344 3663.54   351.6 3663.01  357.56 3663.54
   359.7 3664.22   376.6 3676.82   383.8 3682.73   399.8 3697.95   408.9 3702.96
#Mann= 3, -1 ,  0
       0     0.1       0     344   0.045       0  357.56     0.1       0
Bank Sta=344,357.56
XS Rating Curve= 0 ,0
Exp/Cntr(USF)=0,0
Exp/Cntr=0.3,0.1

Type RM Length L Ch R = 1 ,13138   ,331.9,332.5,329.9
XS GIS Cut Line= 3
2358912.05651997616634.7374609772358923.07390004 616812.00715263
2358881.98341758617011.522399251
#Sta/Elev= 30
       0 3679.94    18.5 3676.45    28.8 3675.71    42.5 3673.12    74.6  3669.3
    82.6 3669.68    94.6 3668.29   106.6 3668.35   114.7 3667.62   158.7 3666.54
   177.7 3666.48   199.2 3663.75   207.4 3660.58   231.6 3660.47   240.1 3659.86
   252.3 3660.31   264.6 3658.69   275.9 3658.99   280.9  3658.3   293.2  3657.5
  297.033658.299   301.3 3659.01   306.4 3658.82   317.7 3660.66   321.7 3662.56
   330.1 3668.47   333.5 3670.98   342.2 3678.91   350.3 3683.94   381.3 3696.31
#Mann= 5, -1 ,  0
       0     0.1       0  267.61    0.08       0   280.9   0.045       0
  297.03    0.08       0  317.61     0.1       0
#XS Ineff= 2 , 0
          250.08 3666.77
Permanent Ineff=
       F       F
Bank Sta=280.9,297.03
XS Rating Curve= 0 ,0
Exp/Cntr(USF)=0,0
Exp/Cntr=0.3,0.1

Type RM Length L Ch R = 1 ,12805   ,305.4,307.2,307.3
XS GIS Cut Line= 3
 2358608.2138157 616660.204201842358595.15365706616925.791526098
2358654.34473671617045.877507223
#Sta/Elev= 30
       0 3673.22      17 3668.88      41  3664.5    77.1 3660.77    92.6 3660.38
   101.1 3659.04   113.1 3655.09   117.1 3654.48   133.1 3653.97   149.2 3654.34
   157.2 3653.68  162.023652.401   165.2 3651.19   169.2 3651.03  174.853652.403
   181.2 3653.66   201.2 3653.19   209.2  3654.3   225.2 3654.06   233.3 3656.18
   245.3 3658.12   265.3 3657.37   304.4  3660.6     311 3660.37     320 3661.15
   332.1 3663.17   363.3 3672.98   372.3 3675.08   394.6 3682.95   399.8 3685.63
#Mann= 5, -1 ,  0
       0     0.1       0  162.02   0.045       0  174.85     0.1       0
     190    0.08       0  285.91     0.1       0
Bank Sta=162.02,174.85
XS Rating Curve= 0 ,0
Exp/Cntr(USF)=0,0
Exp/Cntr=0.3,0.1

Type RM Length L Ch R = 1 ,12498   ,366.9,364.1,352.4
XS GIS Cut Line= 3
2358304.22701556616722.5679971452358309.11238487616977.942697271
2358423.93660358617150.638340408
#Sta/Elev= 30
       0 3664.37    18.6 3658.74    33.9 3650.07    38.6 3648.66    50.6 3648.03
    62.6 3649.74    66.6 3649.78    90.6 3646.74   118.6 3649.38   130.6 3646.73
   142.6 3646.22   154.6 3646.63   162.6 3645.99   182.2 3646.62   206.4 3648.62
   222.7 3648.01   234.7 3648.33   242.7 3651.68   246.7 3652.23   268.9 3652.74
   283.3 3653.93   297.7 3653.71   326.6 3655.69   355.4 3656.21   363.8 3656.98
   379.4 3656.85   398.5 3657.86   418.6  3660.6   424.4 3662.01   462.8 3675.26
#Mann= 5, -1 ,  0
       0     0.1       0     130    0.12       0   154.6   0.045       0
   182.2    0.12       0  275.42     0.1       0
#XS Ineff= 2 , 0
           65.17 3652.22
Permanent Ineff=
       F       F
Bank Sta=154.6,182.2
XS Rating Curve= 0 ,0
Exp/Cntr(USF)=0,0
Exp/Cntr=0.3,0.1

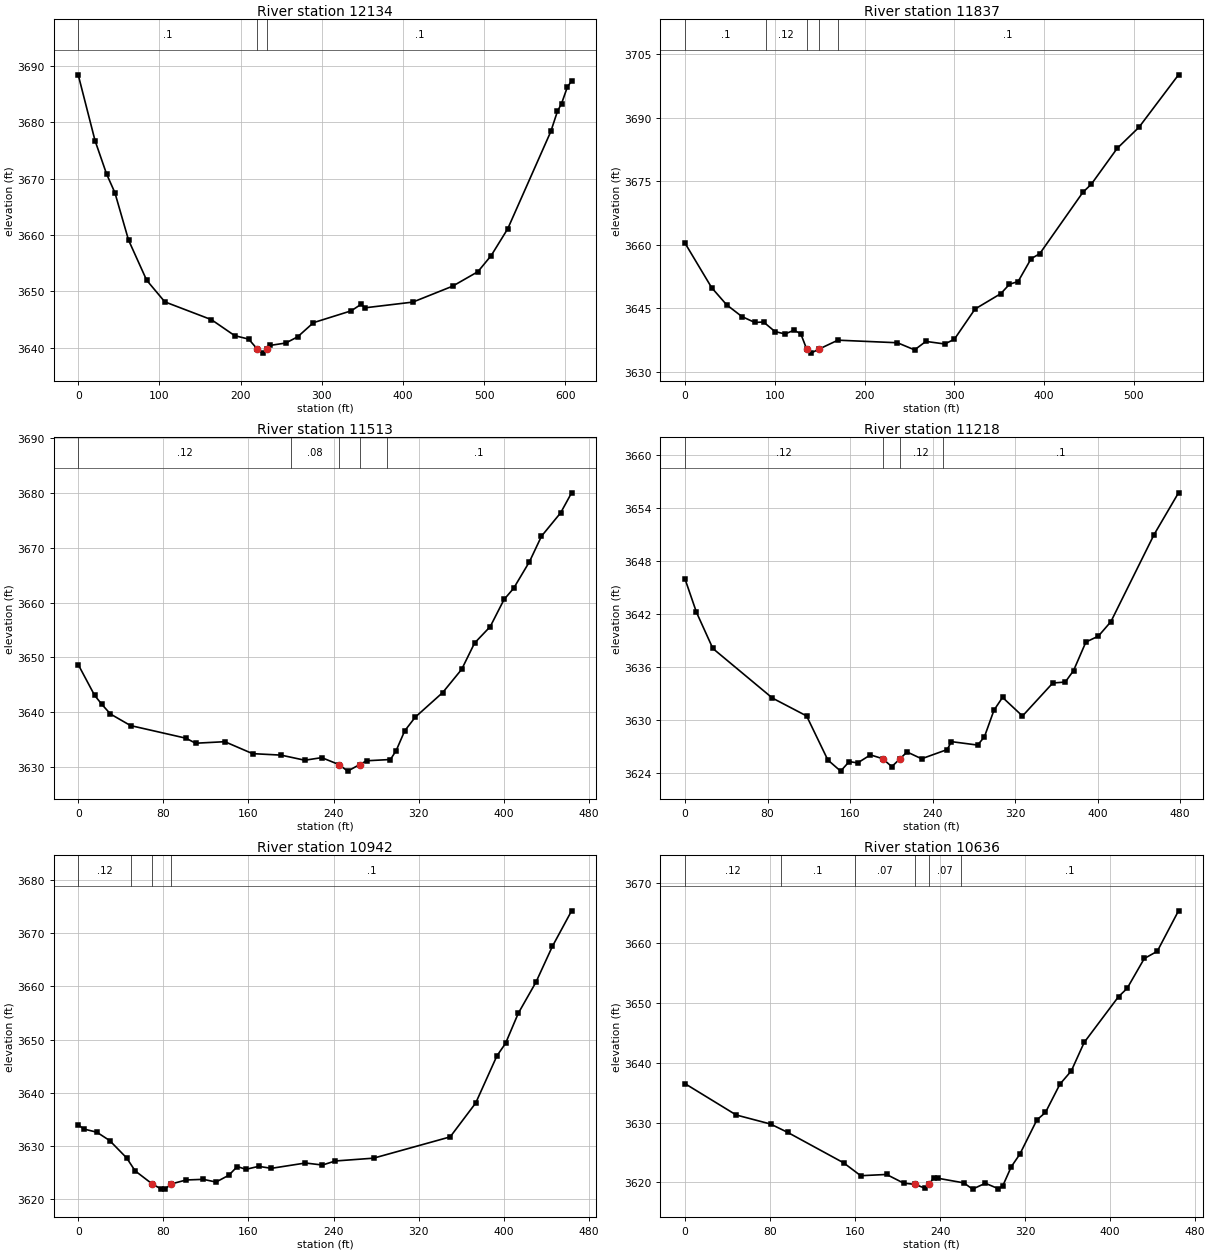
Type RM Length L Ch R = 1 ,12134   ,296.6,297.6,297
XS GIS Cut Line= 3
2357872.48657913616812.2547977592358147.24682402617202.231629677
2358173.77334588617330.227533089
#Sta/Elev= 30
       0 3688.42    20.7 3676.75    34.9 3670.83    45.2 3667.49      62 3659.08
    84.3 3651.96   106.7 3648.11   164.1 3644.95   192.8 3642.11     210  3641.5
   220.43639.759   227.2 3639.01     233 3639.74     236 3640.37   255.6  3640.8
   270.3  3641.9   289.8 3644.42   336.3 3646.52   348.5 3647.68   353.5 3647.06
   412.2 3648.07   461.1 3650.89   492.3 3653.46   508.7 3656.32   529.1 3661.08
   582.2 3678.36   590.4 3681.96   595.4 3683.31   602.6 3686.26   607.8 3687.33
#Mann= 3, -1 ,  0
       0     0.1       0   220.4   0.045       0     233     0.1       0
Bank Sta=220.4,233
XS Rating Curve= 0 ,0
Exp/Cntr(USF)=0,0
Exp/Cntr=0.3,0.1

Type RM Length L Ch R = 1 ,11837   ,317.2,323.4,323.3
XS GIS Cut Line= 2
2357676.53224129617000.5514832722357982.19073263617457.796370255
#Sta/Elev= 30
       0 3660.37    29.6 3649.89    46.3 3645.84    63.3 3643.07    77.7 3641.67
    87.4 3641.79   100.1 3639.53   111.4 3638.95   121.3 3639.84   128.9 3639.02
   135.5 3635.39   140.3 3634.43  149.263635.383   170.3 3637.49   236.7 3636.88
   255.8  3635.2   268.4  3637.2   289.4 3636.59   300.1  3637.7   323.2 3644.85
   351.9 3648.48   361.6  3650.7   371.2 3651.34   385.7 3656.74   395.3 3657.91
   443.4 3672.42   452.8 3674.33   481.6 3682.79     506  3687.8     550 3700.17
#Mann= 5, -1 ,  0
       0     0.1       0      90    0.12       0   135.5   0.045       0
  149.26    0.12       0     170     0.1       0
Bank Sta=135.5,149.26
XS Rating Curve= 0 ,0
Exp/Cntr(USF)=0,0
Exp/Cntr=0.3,0.1

Type RM Length L Ch R = 1 ,11513   ,284.9,295.1,298.7
XS GIS Cut Line= 2
  2357498.255995617162.4139449362357704.74889288617577.666752734
#Sta/Elev= 30
       0 3648.71    15.4  3643.1    22.3 3641.43    30.3 3639.69    49.2 3637.58
   101.4 3635.27   110.3 3634.36   137.8 3634.64   163.9 3632.46   190.7 3632.19
     213 3631.26   228.9 3631.73  245.163630.464   253.3 3629.27   264.53630.464
   271.1 3631.16   293.5 3631.39   298.9 3633.02   306.9 3636.61   316.8 3639.11
   342.6  3643.6   360.5 3647.85   372.6 3652.64   387.3 3655.63   400.3 3660.58
   409.3 3662.62   424.2 3667.48   435.5 3672.13   453.5 3676.39   463.8 3680.04
#Mann= 5, -1 ,  0
       0    0.12       0     200    0.08       0  245.16   0.045       0
   264.5    0.08       0     290     0.1       0
Bank Sta=245.16,264.5
XS Rating Curve= 0 ,0
Exp/Cntr(USF)=0,0
Exp/Cntr=0.3,0.1

Type RM Length L Ch R = 1 ,11218   ,274.1,275.7,270.9
XS GIS Cut Line= 3
2357391.50344113617179.1383004912357309.94391985617495.881525079
2357324.20295989617646.534040984
#Sta/Elev= 30
       0 3645.95      11 3642.21    26.9 3638.11    84.7 3632.49   117.8 3630.47
   138.4 3625.48   150.8 3624.22   159.1  3625.3   167.3 3625.15   179.7 3626.06
   191.43625.636   200.4 3624.73   208.1 3625.59   215.2 3626.39   229.3 3625.62
   254.1 3626.66   258.2 3627.56   283.6 3627.17   290.2  3628.1   299.5 3631.13
   307.8 3632.57   327.1 3630.46   356.5  3634.2   368.6 3634.31   376.6  3635.6
   388.6 3638.84   400.7 3639.51   412.8 3641.14   454.7 3651.01   478.4 3655.74
#Mann= 4, -1 ,  0
       0    0.12       0   191.4   0.045       0   208.1    0.12       0
     250     0.1       0
Bank Sta=191.4,208.1
XS Rating Curve= 0 ,0
Exp/Cntr(USF)=0,0
Exp/Cntr=0.3,0.1

Type RM Length L Ch R = 1 ,10942   ,308.7,306.6,304.8
XS GIS Cut Line= 2
2357124.09395411617195.6442988632357127.88522517617659.182621163
#Sta/Elev= 30
       0 3633.97     5.5 3633.19    17.5  3632.6    29.5 3631.04    45.5 3627.77
    53.5 3625.33    69.5 3622.88    78.1  3621.9    81.5  3621.9   87.493622.882
   101.5 3623.62   117.5 3623.74   129.5 3623.23   141.5 3624.51   149.5 3626.15
   157.5 3625.62   169.5 3626.18   181.5 3625.81   213.5 3626.81   229.5 3626.43
   241.5 3627.19   277.5 3627.72   349.5 3631.72   373.5 3638.09   393.5 3646.98
   401.5 3649.29   413.5 3654.96   430.1  3660.8   445.5 3667.52   463.6 3674.22
#Mann= 4, -1 ,  0
       0    0.12       0      50     0.1       0    69.5   0.045       0
   87.49     0.1       0
Bank Sta=69.5,87.49
XS Rating Curve= 0 ,0
Exp/Cntr(USF)=0,0
Exp/Cntr=0.3,0.1

Type RM Length L Ch R = 1 ,10636   ,200.8,202.2,200
XS GIS Cut Line= 2
2356826.85615131617181.6513917122356895.20757295617641.004342931
#Sta/Elev= 30
       0 3636.49    48.1 3631.27    80.4 3629.76    96.6 3628.36   149.2 3623.28
   165.3 3621.13   189.6 3621.34   205.8 3619.88   216.4 3619.69   225.9 3619.03
   229.33619.682   234.1 3620.76   238.1  3620.7   262.4 3619.93   270.5 3618.89
   282.6 3619.87   294.7 3618.97   298.8 3619.36     307 3622.63     315 3624.71
   331.1 3630.44   339.2  3631.7   352.8 3636.42   363.5 3638.63   375.6 3643.38
     408 3651.04     416  3652.4   432.2  3657.4   444.4  3658.6   464.4 3665.36
#Mann= 6, -1 ,  0
       0    0.12       0      90     0.1       0     160    0.07       0
   216.4   0.045       0   229.3    0.07       0     260     0.1       0
Bank Sta=216.4,229.3
XS Rating Curve= 0 ,0
Exp/Cntr(USF)=0,0
Exp/Cntr=0.3,0.1

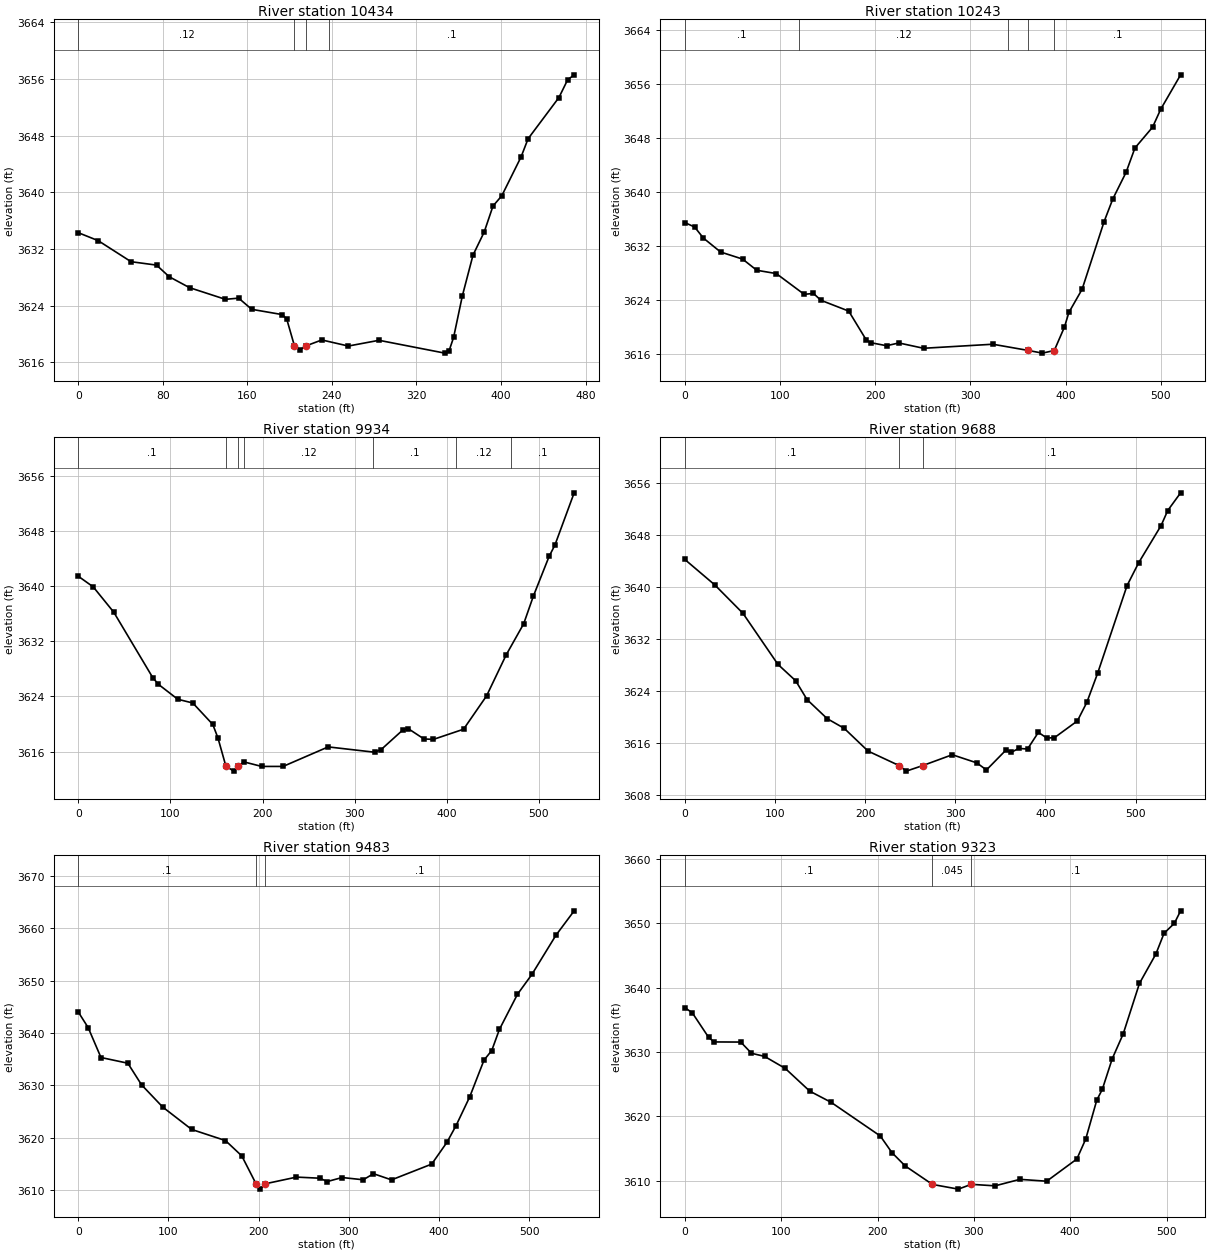
Type RM Length L Ch R = 1 ,10434   ,179.6,190.6,190.3
XS GIS Cut Line= 3
2356658.33226766617203.3480355232356651.22074432617310.020885649
2356747.93746177 617659.19668173
#Sta/Elev= 30
       0 3634.31    18.8 3633.19    49.9 3630.22      74 3629.74      86  3628.1
   105.2 3626.56   139.2 3624.91   151.7 3625.08   164.1  3623.5   193.2 3622.75
   197.3 3622.08   204.5 3618.35   209.8  3617.8  215.613618.352   230.4 3619.18
   255.5 3618.32   284.5 3619.13   346.8 3617.32   350.9 3617.68   355.1 3619.53
   363.4  3625.4   373.5 3631.16   384.1 3634.42   392.4 3638.08   400.7 3639.52
     419 3645.02   425.6 3647.57   454.8 3653.39     463 3655.88   469.2 3656.59
#Mann= 4, -1 ,  0
       0    0.12       0   204.5   0.045       0  215.61    0.12       0
  236.91     0.1       0
Bank Sta=204.5,215.61
XS Rating Curve= 0 ,0
Exp/Cntr(USF)=0,0
Exp/Cntr=0.3,0.1

Type RM Length L Ch R = 1 ,10243   ,298.8,308.8,311.4
XS GIS Cut Line= 2
2356425.70391548617240.2575980292356687.25554828617690.705674719
#Sta/Elev= 30
       0 3635.48    10.3 3634.82    19.6 3633.17    37.6 3631.11    60.7 3630.06
    75.6  3628.4    96.1 3627.91   125.4 3624.83   135.2 3624.96   142.9 3623.95
   172.2 3622.34   190.7 3618.04   195.3 3617.65     212  3617.2   224.9 3617.61
   250.8 3616.82   323.6 3617.42   360.43616.507   375.7  3616.1  388.17 3616.49
   398.9 3619.99   403.5 3622.14   417.4 3625.58   440.5 3635.62   449.7    3639
   463.6 3642.94   472.9 3646.55   491.4 3649.63   499.9 3652.28   520.9 3657.41
#Mann= 5, -1 ,  0
       0     0.1       0     120    0.12       0     340     0.1       0
   360.4   0.045       0  388.17     0.1       0
Bank Sta=360.4,388.17
XS Rating Curve= 0 ,0
Exp/Cntr(USF)=0,0
Exp/Cntr=0.3,0.1

Type RM Length L Ch R = 1 ,9934    ,238,245.8,248
XS GIS Cut Line= 2
2356229.16862624617333.8095305452356594.31376722 617729.45877252
#Sta/Elev= 30
       0  3641.4    16.2 3639.86    38.5 3636.19    80.9  3626.7      87 3625.74
     108 3623.58   124.3 3623.04     146 3619.93   151.6 3617.98   160.2  3613.9
   168.7 3613.17  173.613613.891     180  3614.5   199.1 3613.85   222.3 3613.85
   271.3 3616.68   321.6 3615.91   328.8 3616.29   352.9  3619.2   358.4 3619.31
   375.3 3617.83   385.6 3617.77   418.3 3619.24   443.3 3624.07   464.5 3629.99
   483.6 3634.52   494.2 3638.56   511.2 3644.28   517.5 3645.92   538.4 3653.49
#Mann= 7, -1 ,  0
       0     0.1       0   160.2   0.045       0  173.61     0.1       0
     180    0.12       0     320     0.1       0     410    0.12       0
     470     0.1       0
Bank Sta=160.2,173.61
XS Rating Curve= 0 ,0
Exp/Cntr(USF)=0,0
Exp/Cntr=0.3,0.1

Type RM Length L Ch R = 1 ,9688    ,204.6,205.6,200.8
XS GIS Cut Line= 2
2356133.94009102617444.366681593 2356501.7149942617853.318537672
#Sta/Elev= 30
       0 3644.24    33.3 3640.32    64.5 3635.96   103.3 3628.11     123 3625.59
   135.6  3622.7   157.9 3619.77   176.8 3618.28   203.3 3614.78   237.8 3612.55
   245.7  3611.7  263.823612.548   296.7 3614.22   323.9 3612.97   334.6 3611.88
   356.2 3614.93   361.9 3614.57   370.4 3615.19   380.2  3615.1   392.2 3617.66
   401.5 3616.79     410 3616.84   435.5 3619.42     446 3622.28     458 3626.77
   490.6 3640.23   503.5 3643.74   528.3 3649.44   535.7 3651.76     550 3654.48
#Mann= 3, -1 ,  0
       0     0.1       0   237.8   0.045       0  263.82     0.1       0
Bank Sta=237.8,263.82
XS Rating Curve= 0 ,0
Exp/Cntr(USF)=0,0
Exp/Cntr=0.3,0.1

Type RM Length L Ch R = 1 ,9483    ,147.9,160,167.2
BEGIN DESCRIPTION:
Structure XS 4
END DESCRIPTION:
XS GIS Cut Line= 2
 2356024.7443133617637.3354245662356459.78104936617973.851454308
#Sta/Elev= 30
       0    3644    10.9 3641.03    25.1 3635.31    54.9 3634.22    70.1 3630.09
    93.6 3625.83   125.7 3621.55   163.2 3619.42   181.3 3616.49  197.053611.173
   201.6 3610.13   207.6 3611.16     242 3612.43   267.8 3612.22   276.1 3611.58
   292.6 3612.35     316 3611.92   327.4 3613.08   347.4  3611.9     392 3614.92
   408.9 3619.09     419 3622.28   434.2  3627.8     450 3634.81   458.6 3636.65
   467.1 3640.69   487.1  3647.4   503.1  3651.2   529.8  3658.7     550 3663.37
#Mann= 3, -1 ,  0
       0     0.1       0  197.05   0.045       0   207.6     0.1       0
Bank Sta=197.05,207.6
XS Rating Curve= 0 ,0
Exp/Cntr(USF)=0,0
Exp/Cntr=0.3,0.1

Type RM Length L Ch R = 1 ,9323    ,65.6,60.1,58.8
BEGIN DESCRIPTION:
Structure XS 3
END DESCRIPTION:
XS GIS Cut Line= 2
2355978.47986897617711.5344277462356347.95430465618069.747892477
#Sta/Elev= 30
       0 3636.93     7.9 3636.08    24.6 3632.32    30.2 3631.58    58.1 3631.56
    69.2 3629.82    82.8 3629.33   104.2 3627.47   129.7 3623.93   151.8  3622.2
   202.9 3616.96     215 3614.37   228.7 3612.31     257 3609.43   283.9  3608.7
  297.313609.446     322 3609.21   347.8 3610.22   375.6 3609.93   406.9 3613.38
   416.1 3616.48   427.6 3622.54   433.3  3624.2   443.6 3628.96     455 3632.83
   471.9 3640.69   488.9 3645.24   497.4 3648.47   508.1 3650.02   514.6 3651.96
#Mann= 3, -1 ,  0
       0     0.1       0     257   0.045       0  297.31     0.1       0
Bank Sta=257,297.31
XS Rating Curve= 0 ,0
Exp/Cntr(USF)=0,0
Exp/Cntr=0.3,0.1

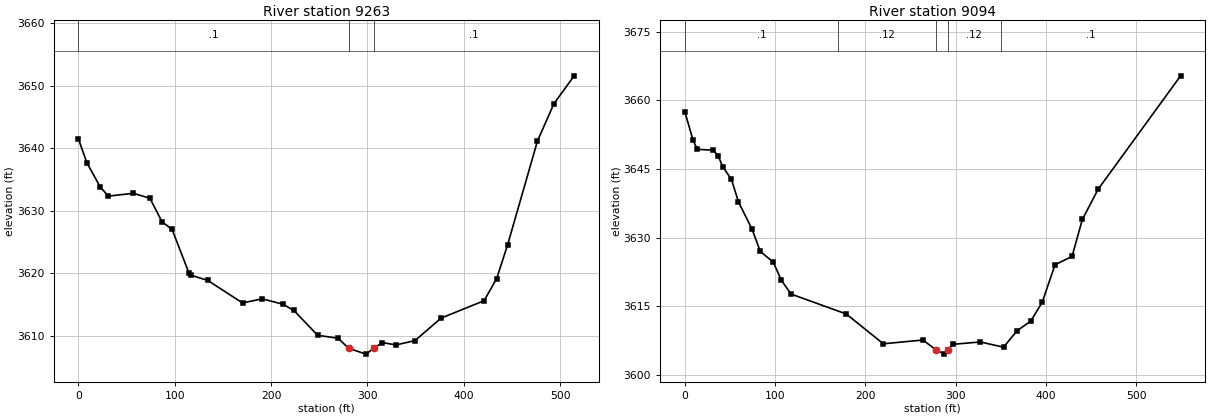
Type RM Length L Ch R = 1 ,9263    ,168,168.5,160.6
BEGIN DESCRIPTION:
Structure XS 2
END DESCRIPTION:
XS GIS Cut Line= 2
2355945.86042965617757.4625516762356315.33486534618115.676016407
#Sta/Elev= 30
       0 3641.55     8.8 3637.71    22.6 3633.86    31.1 3632.36    57.1 3632.81
    74.3 3632.02    86.8 3628.27    97.3 3627.04   114.6 3620.14   117.4 3619.69
   134.4 3618.87   170.4 3615.28     191 3615.93   212.2 3615.08   223.7 3614.07
   248.4  3610.1   269.7 3609.63  280.463608.027   298.5 3607.09  306.733608.025
   315.4 3608.94   329.6 3608.56   349.4 3609.25   376.5 3612.85   421.1 3615.63
   434.2 3619.18   445.6 3624.61   476.5 3641.17   493.6 3647.14   514.6  3651.6
#Mann= 3, -1 ,  0
       0     0.1       0  280.46   0.045       0  306.73     0.1       0
Bank Sta=280.46,306.73
XS Rating Curve= 0 ,0
Exp/Cntr(USF)=0,0
Exp/Cntr=0.3,0.1

Type RM Length L Ch R = 1 ,9094    ,317.5,316.9,315.8
BEGIN DESCRIPTION:
Structure XS 1
END DESCRIPTION:
XS GIS Cut Line= 2
2355836.57413988617937.5818169842356302.08557862618229.389540847
#Sta/Elev= 30
       0 3657.51       9 3651.37    13.7 3649.29    31.3 3649.09    36.9 3647.91
      42 3645.48    51.7 3642.71    59.5 3637.79    74.6 3631.81    83.6    3627
    98.1 3624.62   106.8 3620.76   117.6 3617.68   178.9 3613.32     220 3606.81
   263.9 3607.63   278.3 3605.48   287.5 3604.55  291.39 3605.45   296.9 3606.69
   327.3 3607.21   353.2 3606.07   368.3 3609.68   383.3 3611.75   396.1 3615.91
   410.2 3624.07   429.1 3625.89   440.5 3633.96   457.9 3640.54   549.4 3665.34
#Mann= 5, -1 ,  0
       0     0.1       0     170    0.12       0   278.3   0.045       0
  291.39    0.12       0     350     0.1       0
Bank Sta=278.3,291.39
XS Rating Curve= 0 ,0
Exp/Cntr(USF)=0,0
Exp/Cntr=0.3,0.1