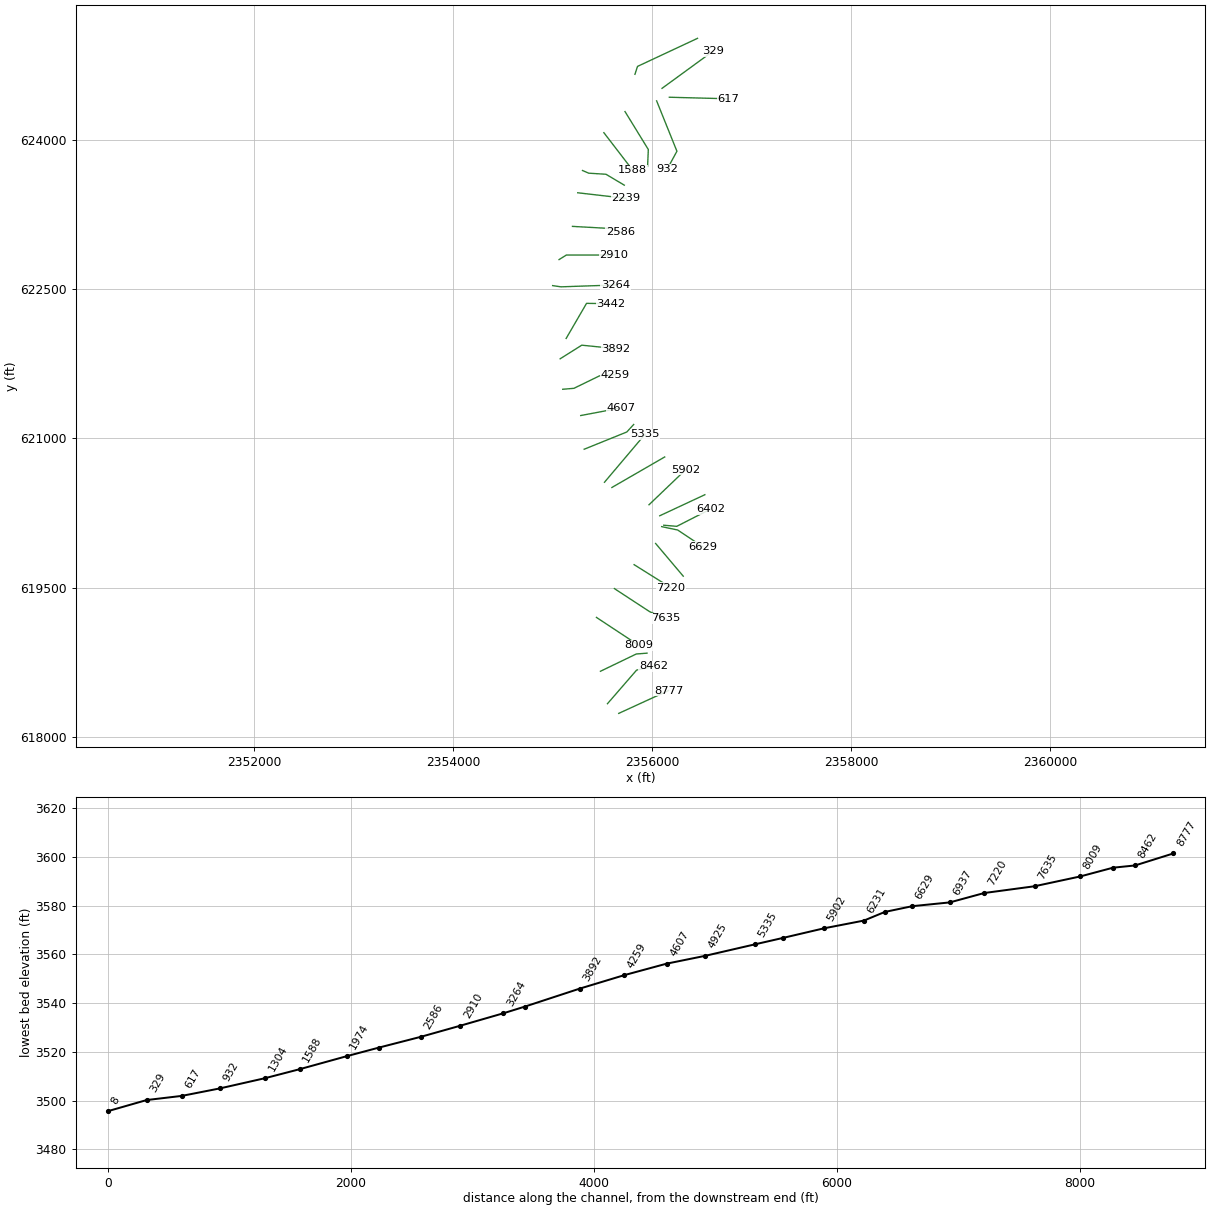
HEC-RAS study GNDYCK_2.prj: GNDYCK_2

--- GNDYCK_2.g01 (geometry) --- (continued)

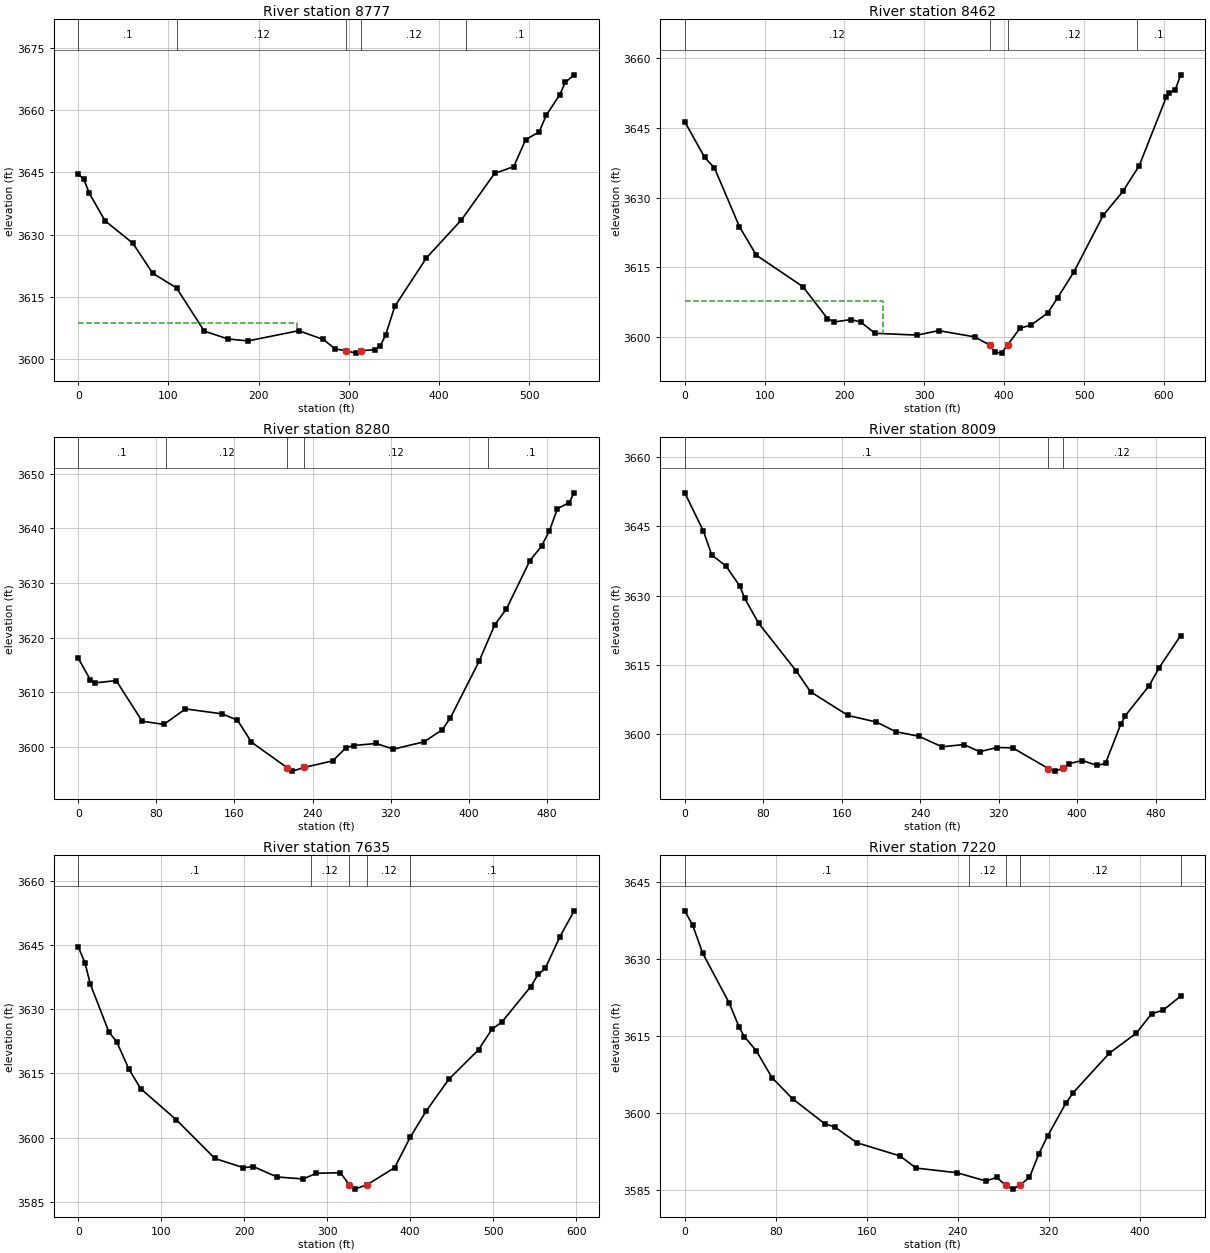
Type RM Length L Ch R = 1 ,8777    ,308.7,315.4,318.6
XS GIS Cut Line= 2
 2355665.1567589618236.1125494722356165.11262874618465.337609651
#Sta/Elev= 30
       0 3644.56     6.1 3643.29    12.2 3639.93    29.7  3633.3    60.5  3627.9
    82.5 3620.68   108.9 3617.15   139.7 3606.73     166 3604.84   188.1 3604.37
   244.4 3606.83   271.7 3604.72   284.9 3602.46   296.43602.035   307.8 3601.43
   313.8 3602.02   328.9 3602.25     335 3603.18     341 3605.86     351 3612.68
   386.2  3624.4   424.9 3633.51   461.7 3644.72     483 3646.37   496.2 3652.88
   511.2 3654.73     519 3658.73   534.1  3663.7   540.1 3666.67     550 3668.49
#Mann= 5, -1 ,  0
       0     0.1       0     110    0.12       0   296.4   0.045       0
   313.8    0.12       0     430     0.1       0
#XS Ineff= 2 , 0
          242.45 3608.69
Permanent Ineff=
       F       F
Bank Sta=296.4,313.8
XS Rating Curve= 0 ,0
Exp/Cntr(USF)=0,0
Exp/Cntr=0.3,0.1

Type RM Length L Ch R = 1 ,8462    ,185,182.3,177.5
XS GIS Cut Line= 3
2355551.88914774618333.4212106782355844.54442929 618670.95030207
2356014.85073334618707.855038294
#Sta/Elev= 30
       0 3646.31    24.9 3638.64    37.1 3636.39    68.5  3623.7    89.7 3617.57
   147.9 3610.81   178.7 3603.93   187.2  3603.2     208 3603.72   220.3 3603.19
   238.2 3600.76   290.9 3600.37   317.9 3601.33     363    3600  381.873598.219
   388.5 3596.68   396.7 3596.49  404.273598.219   419.7 3601.85   433.9 3602.56
   454.5 3605.12   466.8 3608.37   487.3 3613.97   524.1 3626.18   548.7 3631.33
   569.1 3636.84     603  3651.6     606 3652.53   614.2 3653.12     621 3656.43
#Mann= 4, -1 ,  0
       0    0.12       0  381.87   0.045       0  404.27    0.12       0
  566.74     0.1       0
#XS Ineff= 2 , 0
          247.71 3607.68
Permanent Ineff=
       F       F
Bank Sta=381.87,404.27
XS Rating Curve= 0 ,0
Exp/Cntr(USF)=0,0
Exp/Cntr=0.3,0.1

Type RM Length L Ch R = 1 ,8280    ,275.4,270.2,257
XS GIS Cut Line= 3
2355481.22651496618659.3030497242355841.61787648 618832.88622453
2355949.41096276618841.326898395
#Sta/Elev= 30
       0 3616.19    12.2 3612.31    16.6  3611.7    38.8 3612.13    65.4  3604.7
    87.6 3604.11   109.8 3606.95   147.4 3606.04   163.1 3604.88   177.4 3600.87
  213.72 3596.22   219.4 3595.56   231.3 3596.23   260.8 3597.45   274.1 3599.81
   282.3 3600.25   305.2 3600.62   322.9 3599.59   354.2 3600.92     373 3603.14
   381.2 3605.29   410.6 3615.63   426.7 3622.34   438.7 3625.24   462.8 3634.11
   474.8 3636.77   482.8 3639.57   490.9 3643.57   502.9 3644.71   508.1  3646.5
#Mann= 5, -1 ,  0
       0     0.1       0      90    0.12       0  213.72   0.045       0
   231.3    0.12       0  420.02     0.1       0
Bank Sta=213.72,231.3
XS Rating Curve= 0 ,0
Exp/Cntr(USF)=0,0
Exp/Cntr=0.3,0.1

Type RM Length L Ch R = 1 ,8009    ,372.1,374.6,370.1
XS GIS Cut Line= 2
2355441.21974369619200.5527272342355863.10703156618921.950434132
#Sta/Elev= 30
       0 3652.27      19 3643.95    27.5 3638.79    41.9 3636.42    56.3 3632.01
    61.1 3629.38    75.4 3623.98   113.8 3613.62   128.2 3609.16   166.5 3604.02
   195.3  3602.6   215.3  3600.5   238.5 3599.53   262.4 3597.23   284.6 3597.72
   300.7 3596.17   318.2 3597.08   334.3 3597.01  370.73 3592.52     377 3591.96
   385.7 3592.54   391.8 3593.58   405.4 3594.26   420.6 3593.18     429 3593.67
   444.5 3602.08   449.3 3604.01   473.3 3610.41   483.8  3614.4   505.6 3621.33
#Mann= 3, -1 ,  0
       0     0.1       0  370.73   0.045       0   385.7    0.12       0
Bank Sta=370.73,385.7
XS Rating Curve= 0 ,0
Exp/Cntr(USF)=0,0
Exp/Cntr=0.3,0.1

Type RM Length L Ch R = 1 ,7635    ,407.2,414.4,409.7
XS GIS Cut Line= 3
2355621.38312314619490.2475320482355976.48971099619257.793780251
2356136.28532567 619190.89542029
#Sta/Elev= 30
       0 3644.56     8.1 3640.83    14.3 3635.97    36.8 3624.72    46.4 3622.35
    60.7 3616.13      75 3611.47   118.1 3604.17   164.6 3595.12   199.1 3592.97
   210.8 3593.23   239.7 3590.79   271.1 3590.33   286.8 3591.65     316 3591.79
   326.4 3589.02   333.2 3587.95   348.5 3589.03   381.3 3592.97   400.1 3600.09
   419.3  3606.2   446.7 3613.66   482.4 3620.54   498.5 3625.31   510.8 3627.08
   545.5 3635.33   554.2 3638.16   562.8 3639.55   580.5 3646.96   597.7 3653.03
#Mann= 5, -1 ,  0
       0     0.1       0     280    0.12       0   326.4   0.045       0
   348.5    0.12       0     400     0.1       0
Bank Sta=326.4,348.5
XS Rating Curve= 0 ,0
Exp/Cntr(USF)=0,0
Exp/Cntr=0.3,0.1

Type RM Length L Ch R = 1 ,7220    ,290,283.1,278.9
XS GIS Cut Line= 2
2355819.87324926619730.5690431422356189.23100151619499.083400043
#Sta/Elev= 30
       0 3639.41       7 3636.58    15.7 3631.16      39 3621.46    47.8 3616.74
    52.3 3614.91    62.9 3612.12    76.7 3606.88    94.8 3602.77     123 3597.92
   131.8 3597.27   151.4  3594.2   189.2 3591.64   203.3 3589.27   239.2 3588.37
   264.7 3586.76   274.2 3587.45  282.24  3585.9   288.3 3585.17   294.3 3585.88
     303 3587.45   311.4  3592.1     319 3595.54   334.9 3601.88   341.6    3604
   373.3 3611.68   396.9 3615.56   410.4 3619.36   420.5 3620.04   435.9 3622.77
#Mann= 5, -1 ,  0
       0     0.1       0     250    0.12       0  282.24   0.045       0
   294.3    0.12       0   435.9     0.1       0
Bank Sta=282.24,294.3
XS Rating Curve= 0 ,0
Exp/Cntr(USF)=0,0
Exp/Cntr=0.3,0.1

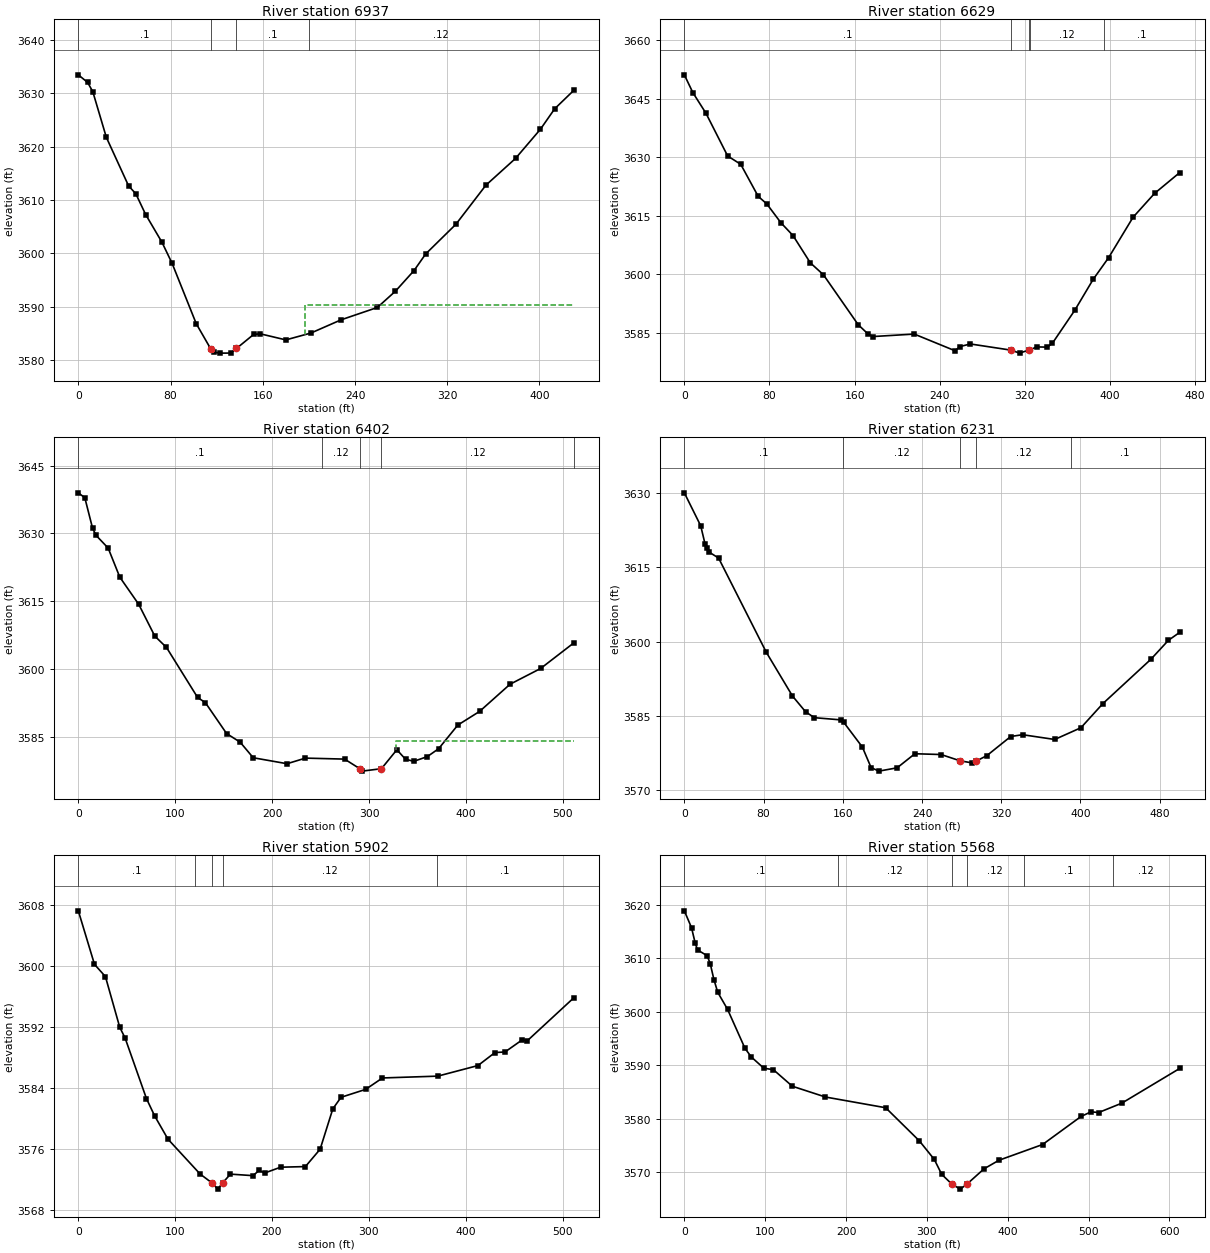
Type RM Length L Ch R = 1 ,6937    ,307.7,308.7,311.1
XS GIS Cut Line= 2
2356036.05487295 619943.36522928 2356313.3212296619615.071710665
#Sta/Elev= 30
       0 3633.48     8.1 3632.05    12.6  3630.3    24.3 3621.77    43.6 3612.67
    49.9 3611.18    58.4  3607.3    72.6 3602.08    81.4 3598.12   102.3 3586.83
  114.683582.178     118 3581.47   123.3 3581.32   132.2 3581.33  137.173582.192
   152.1 3584.83   157.8 3584.94     180  3583.8   201.8 3585.09     228 3587.57
   259.4 3589.88   275.1 3592.94   291.2  3596.8   301.3 3599.91   327.5 3605.47
   353.5 3612.79   379.2 3617.81   400.8 3623.28   413.2 3627.12   429.7 3630.56
#Mann= 4, -1 ,  0
       0     0.1       0  114.68   0.045       0  137.17     0.1       0
     200    0.12       0
#XS Ineff= 2 , 0
                          196.33         3590.35
Permanent Ineff=
       F       F
Bank Sta=114.68,137.17
XS Rating Curve= 0 ,0
Exp/Cntr(USF)=0,0
Exp/Cntr=0.3,0.1

Type RM Length L Ch R = 1 ,6629    ,215.6,226.2,235.7
XS GIS Cut Line= 3
2356096.31176061620112.9797024142356257.31744424620078.922793028
2356507.92300673619912.080132389
#Sta/Elev= 30
       0 3651.18       8 3646.62    20.3 3641.33    40.7 3630.36      53 3628.22
    69.4    3620    77.5 3618.06    90.8 3613.21   102.1 3609.95   118.4 3602.94
   130.7 3599.88   163.4 3587.06   172.8 3584.64   177.6 3584.03   216.1 3584.66
   254.3 3580.39   259.3 3581.47   268.8 3582.12   307.4 3580.52     315 3579.77
   323.7 3580.55   331.4 3581.36     341 3581.31   345.8 3582.26   366.9 3590.75
   384.2 3598.69   398.7 3604.25   421.7 3614.63   441.9 3620.75   465.6 3626.11
#Mann= 5, -1 ,  0
       0     0.1       0   307.4   0.045       0   323.7     0.1       0
  324.57    0.12       0  394.57     0.1       0
Bank Sta=307.4,323.7
XS Rating Curve= 0 ,0
Exp/Cntr(USF)=0,0
Exp/Cntr=0.3,0.1

Type RM Length L Ch R = 1 ,6402    ,169.6,171.6,168.7
XS GIS Cut Line= 3
2356117.52466815620127.1271985732356248.47996989620115.879503946
2356586.71421546620288.611957149
#Sta/Elev= 30
       0 3638.99     6.7 3637.91    14.7 3631.16    18.3 3629.58    30.8 3626.76
    42.8 3620.33    62.3 3614.33    78.9 3607.29      91 3604.77   123.1  3593.7
   131.1 3592.56     153 3585.72     167 3583.81   180.5 3580.36   215.4 3579.04
   234.4 3580.28   274.8 3580.06  290.28 3577.96   292.8  3577.4   312.8 3577.94
   328.7 3582.13   337.7 3580.02   346.2 3579.57   360.2 3580.62   371.8 3582.36
   391.6 3587.59   414.1 3590.62   445.5 3596.63   477.1 3600.12   511.2 3605.76
#Mann= 5, -1 ,  0
       0     0.1       0  251.44    0.12       0  290.28   0.045       0
   312.8    0.12       0  511.23     0.1       0
#XS Ineff= 2 , 0
                           328.2         3584.04
Permanent Ineff=
       F       F
Bank Sta=290.28,312.8
XS Rating Curve= 0 ,0
Exp/Cntr(USF)=0,0
Exp/Cntr=0.3,0.1

Type RM Length L Ch R = 1 ,6231    ,323.2,329,333.3
XS GIS Cut Line= 2
2356077.22532823 620222.098442572356530.54660609620433.646967324
#Sta/Elev= 30
       0 3630.04    16.5  3623.4    20.9 3619.73    22.6 3618.89    25.3 3618.04
    34.6 3616.87    82.8 3597.84   109.2 3589.02   122.4 3585.85   131.3 3584.65
   157.7 3584.21     161  3583.7   179.8 3578.71   188.6 3574.57   196.5 3573.86
   214.9 3574.53   232.8 3577.37   259.3 3577.21   278.63575.934   290.2 3575.54
  295.03 3575.92   305.5 3576.99   329.6 3580.85   341.6 3581.21     374 3580.25
   400.5 3582.62   422.6 3587.48   471.2 3596.45   488.8 3600.26   500.3 3601.88
#Mann= 5, -1 ,  0
       0     0.1       0     160    0.12       0   278.6   0.045       0
  295.03    0.12       0     390     0.1       0
Bank Sta=278.6,295.03
XS Rating Curve= 0 ,0
Exp/Cntr(USF)=0,0
Exp/Cntr=0.3,0.1

Type RM Length L Ch R = 1 ,5902    ,334,333.8,329.9
XS GIS Cut Line= 2
2355969.25814222 620332.551051762356338.84942938620686.243683509
#Sta/Elev= 30
       0 3607.23    16.7  3600.2      28 3598.59    42.8 3591.93    48.3 3590.53
    70.4 3582.56    78.9 3580.28    92.6 3577.24   125.8 3572.66   138.3 3571.47
     144 3570.68  148.92 3571.48   157.1 3572.65   180.3 3572.45   186.7 3573.13
   192.3 3572.79   208.9 3573.56   234.5 3573.64   249.7 3575.92   262.8 3581.22
   271.3 3582.74   296.7 3583.78   314.1 3585.28   371.2 3585.52   412.7 3586.91
   430.3 3588.62   440.6 3588.69     458 3590.25   463.7 3590.17   511.6  3595.8
#Mann= 5, -1 ,  0
       0     0.1       0     120    0.12       0   138.3   0.045       0
  148.92    0.12       0     370     0.1       0
Bank Sta=138.3,148.92
XS Rating Curve= 0 ,0
Exp/Cntr(USF)=0,0
Exp/Cntr=0.3,0.1

Type RM Length L Ch R = 1 ,5568    ,226.4,232.6,235.4
XS GIS Cut Line= 2
2355596.45515176620506.4353550282356127.12684399620813.076154606
#Sta/Elev= 30
       0 3618.93     8.9 3615.77    13.5 3612.83    16.4  3611.6    28.2 3610.52
      32 3609.05    36.6 3606.05    41.3 3603.67    53.5 3600.46      75 3593.17
    82.8 3591.55    98.4 3589.43   110.1 3589.17   133.6 3586.06   174.6 3584.04
   249.1 3582.03   290.7 3575.83   309.2 3572.35   318.4 3569.55     331 3567.71
   341.3 3566.78   349.3 3567.67   370.7 3570.58   389.2 3572.19   443.2 3575.14
   490.8  3580.4   503.2 3581.27   512.5 3581.13   541.1 3582.88   612.9  3589.4
#Mann= 6, -1 ,  0
       0     0.1       0     190    0.12       0     331   0.045       0
   349.3    0.12       0     420     0.1       0     530    0.12       0
Bank Sta=331,349.3
XS Rating Curve= 0 ,0
Exp/Cntr(USF)=0,0
Exp/Cntr=0.3,0.1

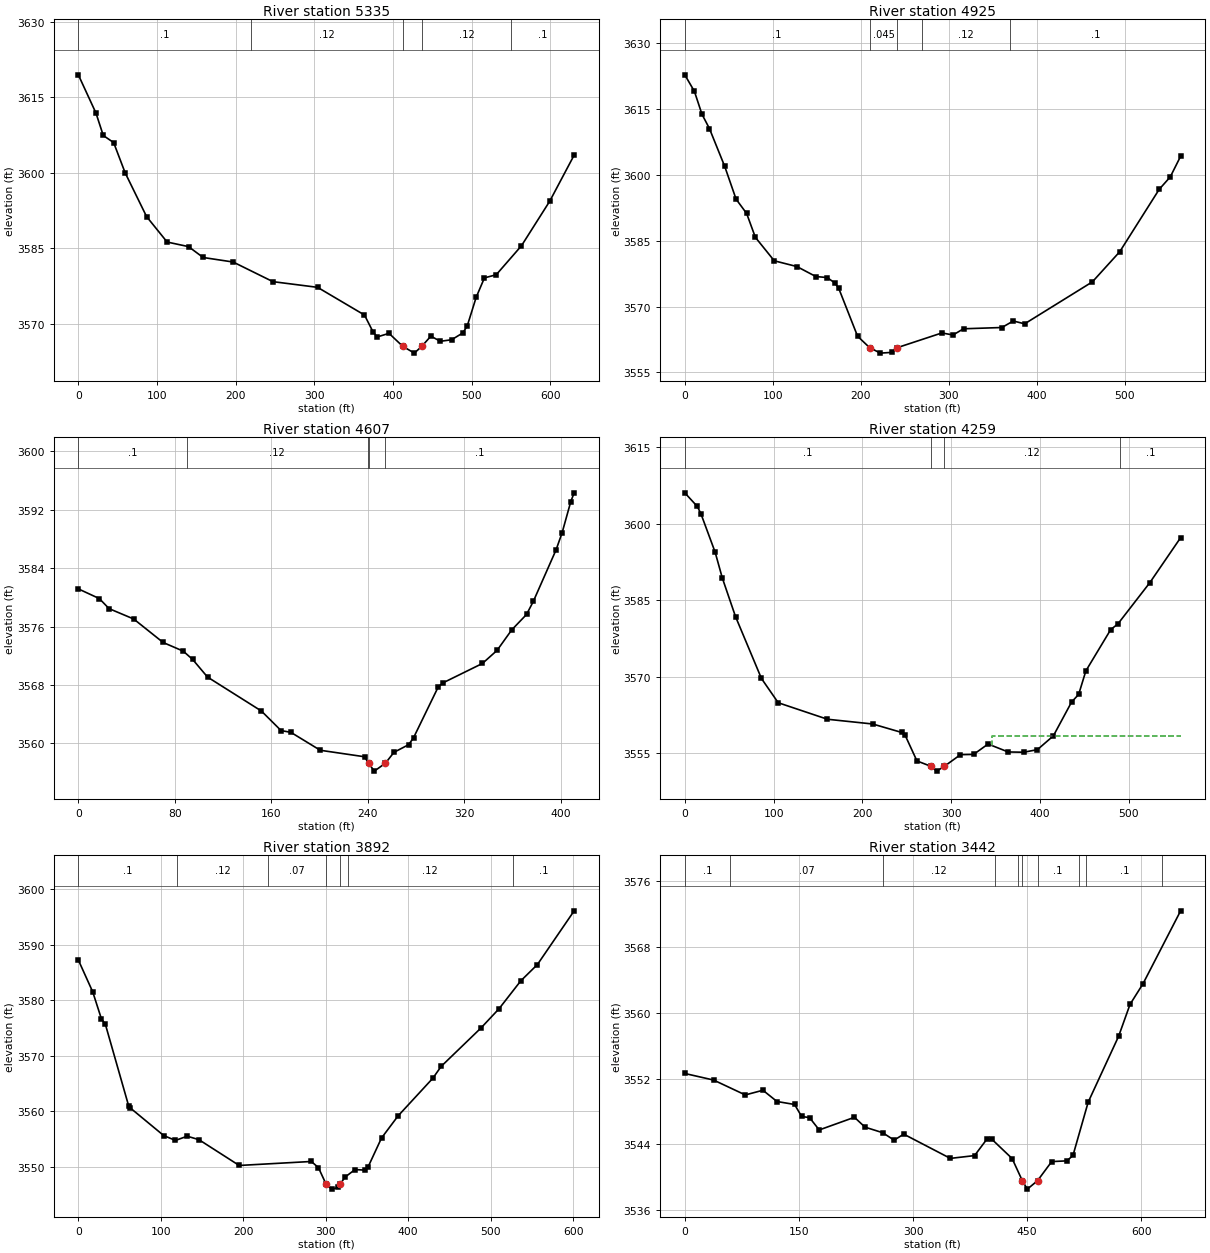
Type RM Length L Ch R = 1 ,5335    ,411.1,410.7,390.2
XS GIS Cut Line= 2
2355521.73296865620558.9306289282355928.78757304621040.338158906
#Sta/Elev= 30
       0 3619.41    22.4 3611.82    31.7 3607.36    44.9 3605.95    59.5 3599.95
    86.8 3591.24   112.9 3586.19   140.1 3585.28   158.7 3583.12   196.8 3582.22
   247.4 3578.32   304.2 3577.19   363.8 3571.69   375.1 3568.22   380.1 3567.34
     395 3568.05  412.283565.496   427.2 3564.12   436.83565.495   448.2 3567.49
   460.3 3566.47   474.6 3566.78   488.7 3568.12   494.4 3569.49   505.8  3575.2
   516.3 3579.07   531.3 3579.69   563.4 3585.45   599.4 3594.32   630.4 3603.46
#Mann= 5, -1 ,  0
       0     0.1       0     220    0.12       0  412.28   0.045       0
   436.8    0.12       0     550     0.1       0
Bank Sta=412.28,436.8
XS Rating Curve= 0 ,0
Exp/Cntr(USF)=0,0
Exp/Cntr=0.3,0.1

Type RM Length L Ch R = 1 ,4925    ,320.2,317.6,310.2
XS GIS Cut Line= 3
2355318.09232255620890.8115801182355746.10201784621064.031966721
2355815.01626429621139.097769833
#Sta/Elev= 30
       0 3622.84    10.9 3619.08    19.5 3613.86      28 3610.59    45.4 3601.95
    58.3 3594.49    70.3 3591.23    80.2 3585.79   101.7 3580.44   127.4 3579.13
     149 3576.85   161.9 3576.62   170.5 3575.39   174.9  3574.2   196.4 3563.24
  210.08 3560.64   222.3 3559.39   235.3 3559.56  241.56 3560.64   292.2 3563.99
   304.9 3563.53   316.8 3564.94   360.4 3565.23   373.4 3566.72   386.3 3566.07
   463.3 3575.64   494.4 3582.51   539.3 3596.75   551.8 3599.56   563.6 3604.28
#Mann= 5, -1 ,  0
       0     0.1       0  210.08   0.045       0  241.56     0.1       0
     270    0.12       0     370     0.1       0
Bank Sta=210.08,241.56
XS Rating Curve= 0 ,0
Exp/Cntr(USF)=0,0
Exp/Cntr=0.3,0.1

Type RM Length L Ch R = 1 ,4607    ,346,348.1,349.6
XS GIS Cut Line= 2
2355283.08158608 621229.28763361 2355686.9453555621306.079768812
#Sta/Elev= 30
       0 3581.16    17.4 3579.83    25.5 3578.45    45.9 3577.03    70.3 3573.81
      87 3572.62    94.8 3571.48   107.1 3569.07   151.8 3564.41   168.1 3561.73
   176.2 3561.49   200.6 3559.03   237.3 3558.14   240.6 3557.27   245.4 3556.17
  254.63 3557.26   261.7 3558.75   273.9  3559.8     278 3560.77   298.3 3567.68
   302.4 3568.28     335 3570.93   347.2 3572.73   359.4 3575.55   371.6 3577.65
   377.2 3579.43   396.1 3586.51   401.1 3588.85   408.3 3593.13   411.1 3594.33
#Mann= 5, -1 ,  0
       0     0.1       0      90    0.12       0     240     0.1       0
   240.6   0.045       0  254.63     0.1       0
Bank Sta=240.6,254.63
XS Rating Curve= 0 ,0
Exp/Cntr(USF)=0,0
Exp/Cntr=0.3,0.1

Type RM Length L Ch R = 1 ,4259    ,370.5,367.2,361.8
XS GIS Cut Line= 4
2355102.14505209621493.4328358222355214.98687725621503.014889051
2355472.95708839621628.7482692742355630.69390469621638.831723137
#Sta/Elev= 30
       0 3606.07    14.1 3603.39    18.1 3601.99    34.2  3594.4    42.2 3589.38
    57.1 3581.79    86.3 3569.64   105.2 3564.88   160.6 3561.64   211.5 3560.71
   244.4 3559.04   248.1  3558.5   261.4 3553.46  276.933552.419   283.7 3551.46
   292.3 3552.41   310.4 3554.69   325.2 3554.74   341.5 3556.78   364.1 3555.22
   381.6 3555.17     397 3555.67     415 3558.38   435.5 3565.01   443.5 3566.52
   451.6 3571.13   479.6 3579.24   487.6 3580.33   523.7 3588.46   558.3 3597.27
#Mann= 4, -1 ,  0
       0     0.1       0  276.93   0.045       0   292.3    0.12       0
  490.23     0.1       0
#XS Ineff= 2 , 0
                          346.25         3558.45
Permanent Ineff=
       F       F
Bank Sta=276.93,292.3
XS Rating Curve= 0 ,0
Exp/Cntr(USF)=0,0
Exp/Cntr=0.3,0.1

Type RM Length L Ch R = 1 ,3892    ,446.9,450,448.2
XS GIS Cut Line= 3
2355076.44464911 621799.850055422355293.71118626 621936.51603298
  2355636.544641621901.680132027
#Sta/Elev= 30
       0 3587.27    17.5  3581.5      28 3576.64    32.8 3575.66    61.1  3560.9
    62.6 3560.62   103.6 3555.58   117.8 3554.71     132 3555.47   146.2 3554.85
   195.1 3550.19   282.6 3550.91   291.2 3549.79  300.52 3546.79   307.4 3545.92
   315.4 3546.22  317.37 3546.79   323.5 3548.09   335.5 3549.45   347.6 3549.35
   351.6 3549.99   367.7 3555.15   387.8 3559.14   429.9 3565.93   440.1 3568.08
   488.3    3575   510.2 3578.47   536.6 3583.51   556.7 3586.44   601.3 3596.14
#Mann= 7, -1 ,  0
       0     0.1       0     120    0.12       0     230    0.07       0
  300.52   0.045       0  317.37    0.07       0  326.68    0.12       0
  526.68     0.1       0
Bank Sta=300.52,317.37
XS Rating Curve= 0 ,0
Exp/Cntr(USF)=0,0
Exp/Cntr=0.3,0.1

Type RM Length L Ch R = 1 ,3442    ,177.3,178.2,178.3
XS GIS Cut Line= 3
2355136.67811975622004.4248437512355341.71033627622356.983039638
2355585.66221152622353.133434738
#Sta/Elev= 30
       0 3552.63    37.9 3551.83    79.5 3550.02   102.7 3550.59   121.2 3549.22
   144.3 3548.86   153.6  3547.4     164 3547.26   176.7 3545.76     223  3547.3
   236.9  3546.1     260 3545.43   275.2 3544.52   287.8 3545.25   349.1  3542.3
   380.9 3542.64   396.8  3544.6   403.4 3544.65   430.3 3542.28  443.73 3539.58
   450.3 3538.56   463.73539.588   482.3 3541.91   502.3    3542   510.3 3542.66
   530.3 3549.15   570.3 3557.16   585.3 3561.04   602.3 3563.54   651.8 3572.42
#Mann= 10, -1 ,  0
       0     0.1       0      60    0.07       0     260    0.12       0
  407.84    0.07       0  437.84     0.1       0  443.73   0.045       0
   463.7     0.1       0  517.84    0.12       0  527.84     0.1       0
  627.84    0.12       0
Bank Sta=443.73,463.7
XS Rating Curve= 0 ,0
Exp/Cntr(USF)=0,0
Exp/Cntr=0.3,0.1

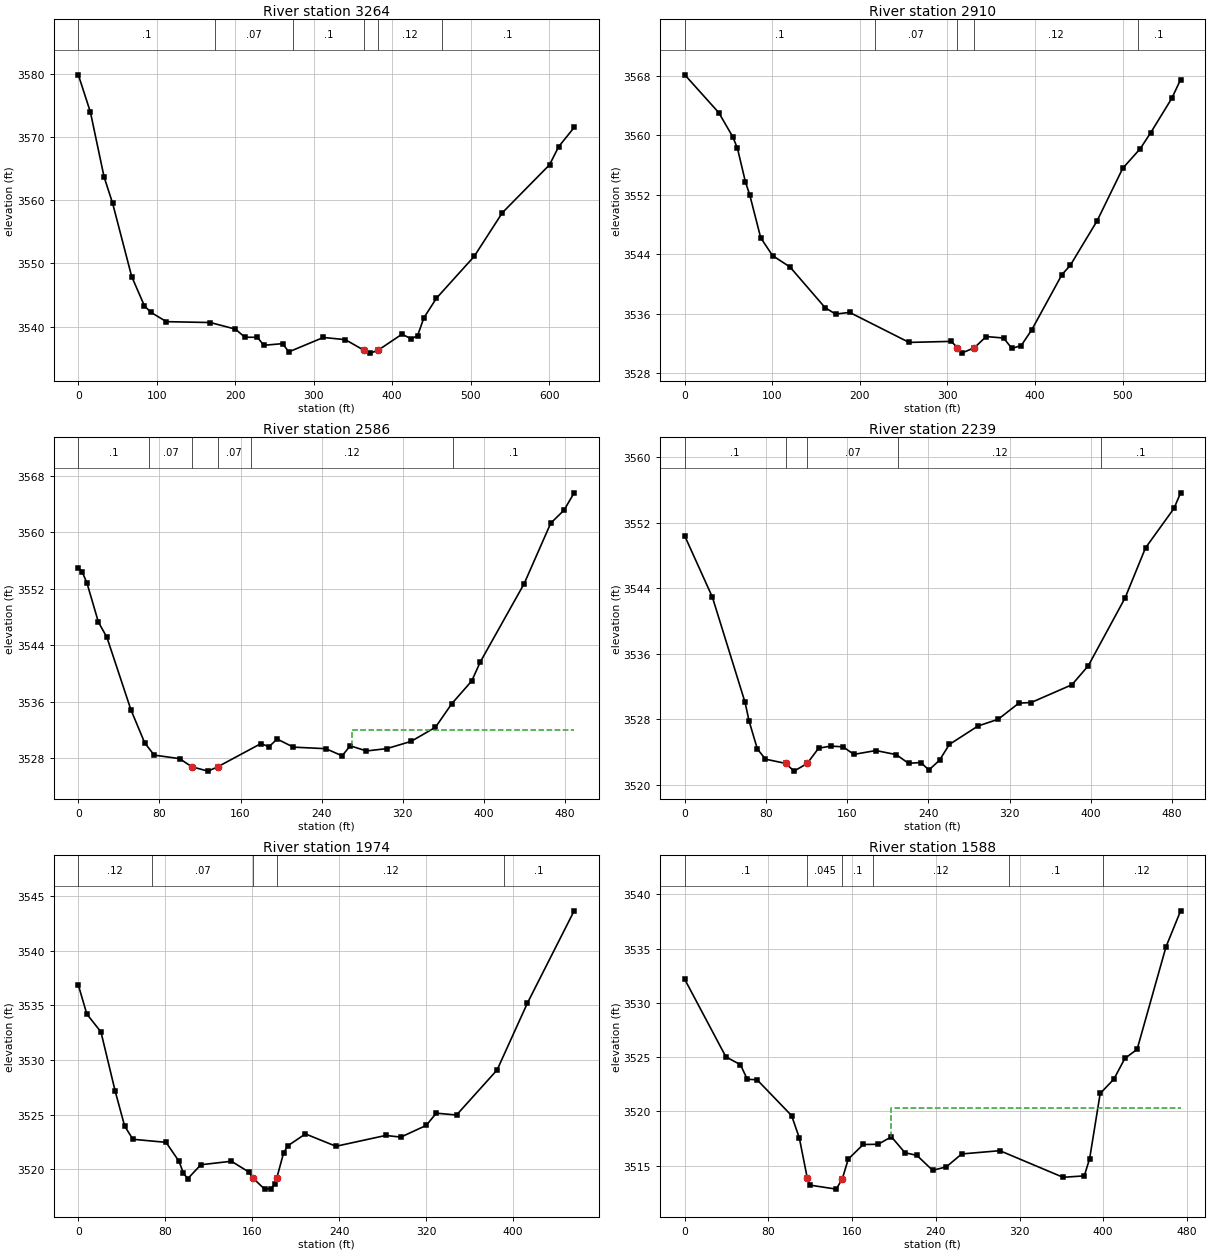
Type RM Length L Ch R = 1 ,3264    ,350.2,353.3,350.5
XS GIS Cut Line= 3
2355000.89546374622535.1811353922355083.83395477622522.972740688
2355631.62781515 622541.58503837
#Sta/Elev= 30
       0 3579.84    15.4 3573.93    32.8 3563.69    43.7 3559.51      68 3547.92
    84.2 3543.29    92.2 3542.28   112.2 3540.78   168.2 3540.64   200.2  3539.6
   212.2 3538.32   228.3  3538.3   236.3 3537.04   260.3  3537.3   268.3    3536
   312.3 3538.28   340.3 3537.93   363.6 3536.28   372.3  3535.8  382.29 3536.28
   412.4 3538.79   424.4 3538.06   432.4 3538.58   440.4 3541.39   456.4 3544.49
   504.5 3551.11   540.4 3558.02   600.5  3565.6   612.2 3568.48   631.9 3571.51
#Mann= 6, -1 ,  0
       0     0.1       0  173.83    0.07       0  273.83     0.1       0
   363.6   0.045       0  382.29    0.12       0  463.83     0.1       0
Bank Sta=363.6,382.29
XS Rating Curve= 0 ,0
Exp/Cntr(USF)=0,0
Exp/Cntr=0.3,0.1

Type RM Length L Ch R = 1 ,2910    ,321.2,324.1,319.3
XS GIS Cut Line= 3
2355065.20545857622796.6596116962355139.11328573622842.725733497
2355618.36670951 622842.40424435
#Sta/Elev= 30
       0 3568.14    38.8 3563.05    54.8  3559.8    60.1 3558.27    69.3 3553.71
    74.2 3551.98    86.7 3546.22   100.2 3543.83   120.2 3542.29   160.2 3536.83
   172.2 3535.96   188.2 3536.19   256.2 3532.15   304.2 3532.29   311.43531.464
   316.2 3530.71   330.8 3531.44   344.2 3532.94   364.2 3532.74   373.5 3531.35
   384.2 3531.72   396.2 3533.83   430.8 3541.28   440.2  3542.5   470.9  3548.5
   500.2 3555.57   520.2 3558.21   532.2 3560.37   556.2 3564.98   566.3  3567.5
#Mann= 5, -1 ,  0
       0     0.1       0  217.09    0.07       0   311.4   0.045       0
   330.8    0.12       0  517.09     0.1       0
Bank Sta=311.4,330.8
XS Rating Curve= 0 ,0
Exp/Cntr(USF)=0,0
Exp/Cntr=0.3,0.1

Type RM Length L Ch R = 1 ,2586    ,346.4,347.6,344.8
XS GIS Cut Line= 3
2355200.38369014623130.4159279872355599.77437707623108.283303795
2355681.28984532623072.439653256
#Sta/Elev= 30
       0    3555     3.8 3554.41     8.6 3552.78    19.8 3547.28    28.2 3545.12
    51.9 3534.84    65.5 3530.16    74.8 3528.43    99.9 3527.93     112 3526.77
     128 3526.16   137.6 3526.78   180.1 3530.06   188.1 3529.62   196.1 3530.71
   212.1 3529.56   244.2 3529.34   260.2 3528.33   268.2 3529.75   284.2 3529.02
   304.3 3529.35   328.3 3530.38   352.3 3532.38   368.4 3535.72   388.1 3538.95
   396.4 3541.61   439.8 3552.74     466 3561.31   479.1 3563.15   489.1 3565.61
#Mann= 6, -1 ,  0
       0     0.1       0      70    0.07       0     112   0.045       0
   137.6    0.07       0     170    0.12       0     370     0.1       0
#XS Ineff= 2 , 0
                          270.28         3531.96
Permanent Ineff=
       F       F
Bank Sta=112,137.6
XS Rating Curve= 0 ,0
Exp/Cntr(USF)=0,0
Exp/Cntr=0.3,0.1

Type RM Length L Ch R = 1 ,2239    ,262.3,264.3,264
XS GIS Cut Line= 2
2355253.15797895623468.2414891052355738.51838236 623412.32216885
#Sta/Elev= 30
       0 3550.35    27.2  3542.9    59.4 3530.07    63.4 3527.78    71.5  3524.4
    79.5 3523.16    99.4 3522.64   107.7  3521.7  120.66 3522.64   131.9  3524.5
     144 3524.75     156 3524.66   166.6 3523.74   188.3 3524.21   208.4 3523.71
   220.5 3522.65   232.5 3522.75   240.6 3521.84     251 3523.03   260.7 3524.95
   288.9  3527.2   308.8 3528.02   329.2 3529.99   341.3 3530.06   381.5 3532.23
   397.6 3534.54   433.9 3542.82     454 3548.91   482.1 3553.73   488.6 3555.62
#Mann= 5, -1 ,  0
       0     0.1       0    99.4   0.045       0  120.66    0.07       0
     210    0.12       0     410     0.1       0
Bank Sta=99.4,120.66
XS Rating Curve= 0 ,0
Exp/Cntr(USF)=0,0
Exp/Cntr=0.3,0.1

Type RM Length L Ch R = 1 ,1974    ,395.9,386.4,371.8
XS GIS Cut Line= 4
2355301.03599721623691.9785278162355363.58640092623665.143522357
2355537.01175295623654.3044378552355721.14736216623544.691837171
#Sta/Elev= 30
       0 3536.85     7.8  3534.2    20.8 3532.56    33.9 3527.14    42.6 3523.95
    50.2 3522.74    80.7 3522.46    92.7 3520.71    96.7 3519.62   100.7 3519.14
   112.7 3520.41   140.8 3520.73   156.8 3519.75   160.8 3519.18   171.3 3518.18
   176.9 3518.22   180.9 3518.62  182.653519.237   188.9 3521.52   192.9 3522.16
   208.9 3523.23     237  3522.1   282.7 3523.09   296.7 3522.94     320 3524.01
   329.3 3525.13   347.9 3524.96   385.2 3529.08   413.1  3535.2   456.1 3543.64
#Mann= 5, -1 ,  0
       0    0.12       0   68.06    0.07       0   160.8   0.045       0
  182.65    0.12       0  391.83     0.1       0
Bank Sta=160.8,182.65
XS Rating Curve= 0 ,0
Exp/Cntr(USF)=0,0
Exp/Cntr=0.3,0.1

Type RM Length L Ch R = 1 ,1588    ,283.7,283.6,280.9
XS GIS Cut Line= 2
2355515.76888838624071.9526203852355804.70639967623696.168874975
#Sta/Elev= 30
       0 3532.16    39.3 3525.03    53.2 3524.31    59.7 3522.97    69.1 3522.92
   102.1 3519.62   109.5 3517.56  117.163513.833   119.5 3513.22   144.8 3512.85
   150.6 3513.81   156.3 3515.62   170.6 3516.96   184.8 3516.98   197.5 3517.67
   210.5  3516.2   221.9 3515.96   236.9 3514.58     250  3514.9   264.7 3516.09
   301.2 3516.39   361.6 3513.94   381.9 3514.07     387 3515.65   397.1 3521.66
   410.2 3522.98   420.7 3524.89   432.4 3525.72     460 3535.16     474 3538.48
#Mann= 6, -1 ,  0
       0     0.1       0  117.16   0.045       0   150.6     0.1       0
     180    0.12       0     310     0.1       0     400    0.12       0
#XS Ineff= 2 , 0
                          197.29         3520.36
Permanent Ineff=
       F       F
Bank Sta=117.16,150.6
XS Rating Curve= 0 ,0
Exp/Cntr(USF)=0,0
Exp/Cntr=0.3,0.1

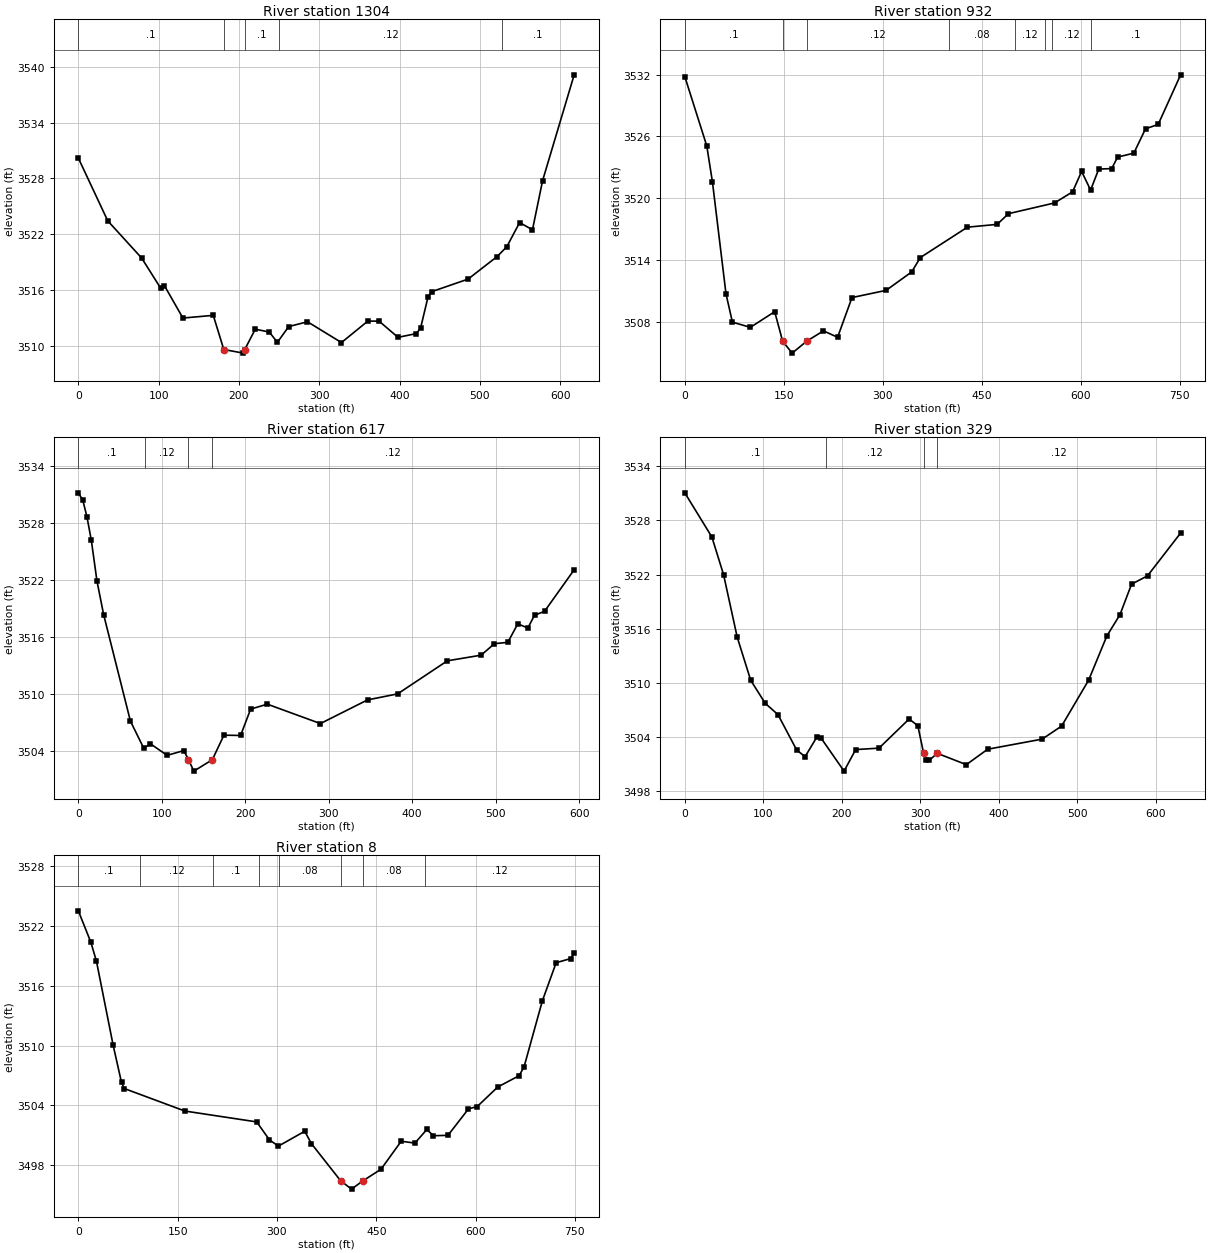
Type RM Length L Ch R = 1 ,1304    ,365.5,372.6,361.6
XS GIS Cut Line= 3
2355728.27142396624284.3269641012355962.37201685623903.105683743
2355955.12198885623733.357818689
#Sta/Elev= 30
       0  3530.2    36.6 3523.44    78.8 3519.43   102.3 3516.21   107.2 3516.45
   130.2 3512.96     168 3513.25  181.09 3509.57   205.5 3509.18  207.21 3509.57
   220.3 3511.76   237.8 3511.45   247.8 3510.34   261.9 3512.04   285.3 3512.56
   327.6 3510.32   360.4 3512.63   374.4 3512.63     398 3510.88     421 3511.29
   426.2 3511.92   435.5 3515.28   440.2 3515.81   485.3 3517.16   521.4 3519.59
   533.4 3520.64   549.4 3523.25   565.4 3522.47     578 3527.77   617.3 3539.17
#Mann= 5, -1 ,  0
       0     0.1       0  181.09   0.045       0  207.21     0.1       0
     250    0.12       0  527.36     0.1       0
#XS Ineff= 2 , 0
                          368.64         3512.29
Permanent Ineff=
       F       F
Bank Sta=181.09,207.21
XS Rating Curve= 0 ,0
Exp/Cntr(USF)=0,0
Exp/Cntr=0.3,0.1

Type RM Length L Ch R = 1 ,932     ,297.4,314.4,331.1
XS GIS Cut Line= 3
2356045.85660239624392.0773861932356249.88061251623885.783085131
2356151.98023747623705.312101411
#Sta/Elev= 30
       0  3531.8    33.3 3525.07    41.9 3521.57    62.4 3510.73    72.1 3507.98
    99.3 3507.47   136.2 3508.99  148.273506.116   162.7 3504.97  184.453506.118
     210 3507.13   231.5 3506.51   253.3 3510.36     305 3511.06   343.8 3512.85
   356.8 3514.24   428.2 3517.19   473.2 3517.46   490.4  3518.5   560.2 3519.54
   587.5 3520.62   601.2  3522.6   614.8 3520.79   627.2 3522.83   646.7 3522.87
   655.8 3523.99   680.3 3524.37     698 3526.73   717.2 3527.16   751.2 3531.97
#Mann= 8, -1 ,  0
       0     0.1       0  148.27   0.045       0  184.45    0.12       0
     400    0.08       0     500    0.12       0  545.86    0.08       0
  555.86    0.12       0  615.86     0.1       0
Bank Sta=148.27,184.45
XS Rating Curve= 0 ,0
Exp/Cntr(USF)=0,0
Exp/Cntr=0.3,0.1

Type RM Length L Ch R = 1 ,617     ,281.4,288.3,290.7
XS GIS Cut Line= 2
2356173.84149936624428.3703772392356767.60208172624412.770003291
#Sta/Elev= 30
       0 3531.15     5.4 3530.36    10.3 3528.64    15.6 3526.14    22.3 3521.89
    30.3 3518.35    62.4 3507.15    78.4 3504.29    86.4 3504.76   106.4 3503.55
   126.4 3504.05  131.843503.112   138.4 3501.89  160.563503.094   174.4 3505.67
   194.4 3505.64   206.4 3508.41   226.4 3508.93     290 3506.89   346.5 3509.38
   382.5 3510.01   442.1 3513.49   482.5 3514.08   498.5 3515.29   514.5 3515.43
   526.5 3517.38   538.5 3516.93   546.5 3518.28   558.5 3518.69     594 3523.06
#Mann= 4, -1 ,  0
       0     0.1       0      80    0.12       0  131.84   0.045       0
  160.56    0.12       0
Bank Sta=131.84,160.56
XS Rating Curve= 0 ,0
Exp/Cntr(USF)=0,0
Exp/Cntr=0.3,0.1

Type RM Length L Ch R = 1 ,329     ,322.9,320.7,311.3
XS GIS Cut Line= 2
2356100.27609629624517.8160179942356610.65470213624890.019496584
#Sta/Elev= 30
       0 3531.06    34.5 3526.16    49.4 3521.98    66.8 3515.04      84 3510.26
   102.5 3507.71   118.7 3506.46   142.6 3502.52   153.3  3501.8   168.2 3503.96
   173.1 3503.92   202.9 3500.19   217.7 3502.58   247.4 3502.74   285.8 3505.97
   296.9 3505.23  304.29 3502.15   306.8 3501.39   311.2 3501.37   321.63502.167
   358.7 3500.91   385.9 3502.62   455.3 3503.74   480.1 3505.19   514.5 3510.28
   537.7 3515.18   554.4 3517.54   569.2 3520.93   589.5 3521.85   631.7  3526.6
#Mann= 4, -1 ,  0
       0     0.1       0     180    0.12       0  304.29   0.045       0
   321.6    0.12       0
Bank Sta=304.29,321.6
XS Rating Curve= 0 ,0
Exp/Cntr(USF)=0,0
Exp/Cntr=0.3,0.1

Type RM Length L Ch R = 1 ,8       ,,,
XS GIS Cut Line= 3
2355828.20036209624659.1405364542355853.72793297624738.231639469
2356456.72845621 625020.38313824
#Sta/Elev= 30
       0 3523.54      19 3520.37    27.4 3518.47    52.6 3510.04    65.2 3506.31
    69.4  3505.7   160.9 3503.44   269.4 3502.35   288.7 3500.54   302.2 3499.92
     342 3501.41   351.9 3500.18  396.043496.454   412.6  3495.6   429.8 3496.43
   457.2  3497.6   487.7 3500.41   508.4 3500.22   526.4 3501.59   536.3 3500.96
   558.3    3501   589.3 3503.66   602.5 3503.89   633.4 3505.85   665.8 3506.99
   673.2 3507.87   700.9 3514.51   721.7 3518.33   743.8 3518.75   748.9  3519.3
#Mann= 8, -1 ,  0
       0     0.1       0   93.11    0.12       0  203.11     0.1       0
  273.11    0.12       0  303.11    0.08       0  396.04   0.045       0
   429.8    0.08       0  523.11    0.12       0
Bank Sta=396.04,429.8
XS Rating Curve= 0 ,0
Exp/Cntr(USF)=0,0
Exp/Cntr=0.3,0.1
LCMann Table=0

Chan Stop Cuts=-1
Use User Specified Reach Order=0
Composite Channel Slope=5